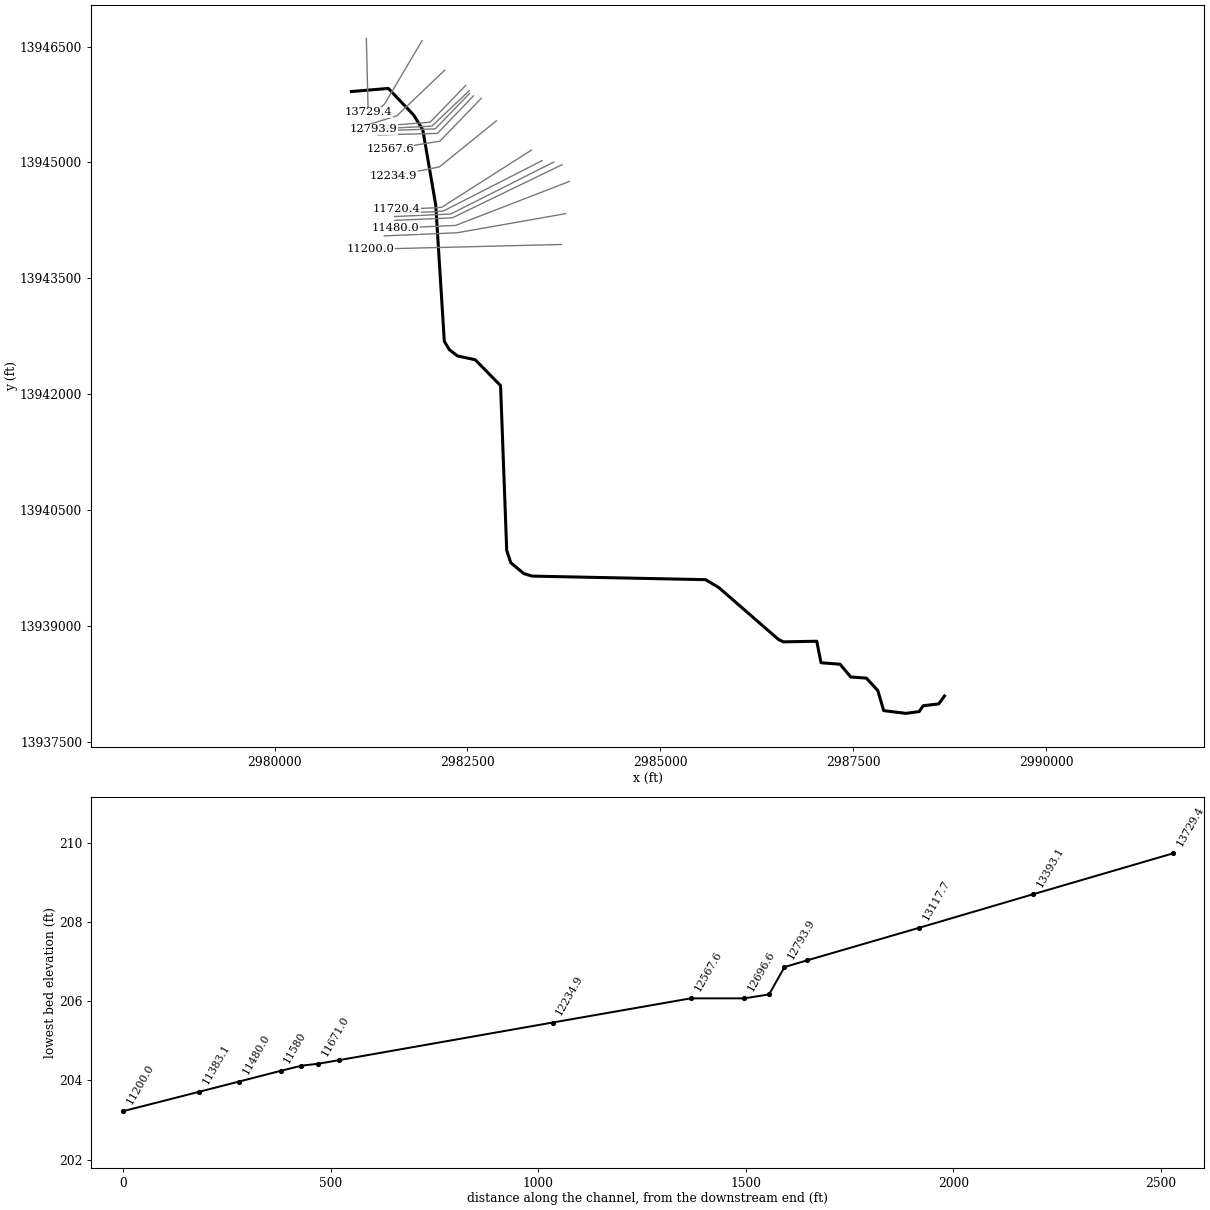
--- L114-01-00.PRJ (project) ---

Proj Title=L114-01-00
Current Plan=p03
Default Exp/Contr=.3,.1
English Units
Geom File=g01
Flow File=f02
Flow File=f03
Plan File=p02
Plan File=p03
Y Axis Title=Elevation
X Axis Title(PF)=Main Channel Distance
X Axis Title(XS)=Station
BEGIN DESCRIPTION:
Little Cypress Creek
Tributary 0.12 of Tributary 13.92 to Little Cypress
HCFCD Unit L114-01-00
Flood Hazard Model
10, 2, 1, 0.50-% Event
Filename L114-01-00.prj
Prepared by: Halff Associates, Inc. Date: 03/24/2004
Reviewed by:    Date:
STATUS Final RAS
END DESCRIPTION:
DSS File=dss
DSS Export Rating Curves= 0
DSS Export Rating Curve Sorted= 0
DSS Export Volume Flow Curves= 0
DXF OffsetX= 0
DXF OffsetY= 0
DXF ScaleX= 1
DXF ScaleY= 10

--- L114-01-00.p03 (plan) ---

Plan Title=Floodway
Version=Version 3.0.1  Mar 2001
Short Identifier=Floodway0607
Geom File=g01
Flow File=f03
Subcritical Flow
K Sum by GR= 0
Std Step Tol= 0.01
Critical Tol= 0.01
Num of Std Step Trials= 20
Max Error Tol= 0.3
Flow Tol Ratio= 0.001
Split Flow NTrial= 30
Split Flow Tol= 0.02
Split Flow Ratio= 0.02
Log Output Level= 0
Friction Slope Method= 1
Unsteady Friction Slope Method= 2
Parabolic Critical Depth
Global Vel Dist= 0 , 0 , 0
Global Log Level= 0
CheckData=True
Encroach Param= 0 ,0,0, 2
Encroach River=L114-01-00
Encroach Reach=Reach - 1
Encroach Node=13729.4
       1  4975.4  5017.2
Encroach Node=13393.1
       1  4985.4  5009.2
Encroach Node=13117.7
       1  4985.4  5009.2
Encroach Node=12848.7
       1  4987.8  5015.1
Encroach Node=12793.9
       1  4980.2  5015.1
Encroach Node=12775.4
       1  4980.2  5015.1
Encroach Node=12756.9
       1  4980.2  5015.1
Encroach Node=12696.6
       1  4987.8  5015.1
Encroach Node=12567.6
       1  4953.2  5033.2
Encroach Node=12234.9
       1  4973.3  5026.4
Encroach Node=11720.4
       1  4973.3  5026.4
Encroach Node=11671.0
       1 4991.07 5010.32
Encroach Node=11650.5
       1 4991.07 5010.32
Encroach Node=11630.0
       1 4991.07 5010.32
Encroach Node=11580
       1  4967.8  5017.8
Encroach Node=11480.0
       1  4967.8  5017.8
Encroach Node=11383.1
       1  4967.8  5017.8
Encroach Node=11200.0
       1  4986.1  5016.1
Encroach Node=11113.3
       1  4986.1  5016.1
Encroach Node=11085.3
       1  4986.1  5016.1
Encroach Node=11057.3
       1  4986.1  5016.1
Encroach Node=10966.1
       1  4986.1  5016.1
Encroach Node=10393.2
       1 4988.51 5006.72
Encroach Node=9910.5
       1  4982.2  5023.2
Encroach Node=9645.0
       1  4977.3  5018.1
Encroach Node=9625.5
       1  4977.3  5018.1
Encroach Node=9606.0
       1  4977.3  5018.1
Encroach Node=9228.7
       1 4984.82 5014.17
Encroach Node=8694.5
       1 4984.06 5015.46
Encroach Node=8348.3
       1 4993.01 5009.05
Encroach Node=7889.1
       1 4984.47 5021.17
Encroach Node=7552.0
       1 4963.65  5021.8
Encroach Node=7080.4
       1    4900    5014
Encroach Node=6578.9
       1    4710    5035
Encroach Node=6318.8
       1    4740    5180
Encroach Node=6204.4
       1    4905    5225
Encroach Node=6159
       1    4905    5225
Encroach Node=6119.8
       1    4905    5225
Encroach Node=6035.2
       1    4905    5280
Encroach Node=5906.9
       1    4965    5269
Encroach Node=5755.1
       1    4945    5405
Encroach Node=5557.0
       1    4935    5475
Encroach Node=5369.4
       1 4981.49    5250
Encroach Node=5352.9
       1 4981.49    5250
Encroach Node=5336.4
       1 4981.49    5250
Encroach Node=5254.6
       1    4975    5250
Encroach Node=5100.0
       1 4984.32    5190
Encroach Node=4853.0
       1    4900    5150
Encroach Node=4725.3
       1    4875    5200
Encroach Node=4707.3
       1    4875    5200
Encroach Node=4689.3
       1    4875    5200
Encroach Node=4620.6
       1    4870    5200
Encroach Node=4393.1
       1    4825    5215
Encroach Node=4179.8
       1    4900    5180
Encroach Node=3911.4
       1    4900    5120
Encroach Node=3251.4
       1    4900    5100
Encroach Node=2784.0
       1    4845    5110
Encroach Node=2705.9
       1    4850    5115
Encroach Node=2674.9
       1    4850    5115
Encroach Node=2643.9
       1    4850    5115
Encroach Node=2552.8
       1    4870    5115
Encroach Node=2377.0
       1    4880    5190
Encroach Node=2236.4
       1  4808.5  5048.5
Encroach Node=2205.4
       1  4808.5  5048.5
Encroach Node=2174.4
       1  4808.5  5048.5
Encroach Node=2094.0
       1    4625 5036.64
Encroach Node=1718.7
       1    4760    5135
Encroach Node=1443.8
       1 4855.22    5261
Encroach Node=755.7
       1    4845    5035
Encroach Reach=L114-01-00_0008
Encroach Node=13729.4
       1  4975.4  5017.2
Encroach Node=13393.1
       1  4985.4  5009.2
Encroach Node=13117.7
       1  4985.4  5009.2
Encroach Node=12848.7
       1  4987.8  5015.1
Encroach Node=12793.9
       1  4980.2  5015.1
Encroach Node=12775.4
       1  4980.2  5015.1
Encroach Node=12756.9
       1  4980.2  5015.1
Encroach Node=12696.6
       1  4987.8  5015.1
Encroach Node=12567.6
       1  4953.2  5033.2
Encroach Node=12234.9
       1  4973.3  5026.4
Encroach Node=11720.4
       1  4973.3  5026.4
Encroach Node=11671.0
       1 4991.07 5010.32
Encroach Node=11650.5
       1 4991.07 5010.32
Encroach Node=11630.0
       1 4991.07 5010.32
Encroach Node=11580
       1  4967.8  5017.8
Encroach Node=11480.0
       1  4967.8  5017.8
Encroach Node=11383.1
       1  4967.8  5017.8
Encroach Node=11200.0
       1  4986.1  5016.1
Encroach Node=11113.3
       1  4986.1  5016.1
Encroach Node=11085.3
       1  4986.1  5016.1
Encroach Node=11057.3
       1  4986.1  5016.1
Encroach Node=10966.1
       1  4986.1  5016.1
Encroach Node=10393.2
       1 4988.51 5006.72
Encroach Node=9910.5
       1  4982.2  5023.2
Encroach Node=9645.0
       1  4977.3  5018.1
Encroach Node=9625.5
       1  4977.3  5018.1
Encroach Node=9606.0
       1  4977.3  5018.1
Encroach Node=9228.7
       1 4984.82 5014.17
Encroach Node=8694.5
       1 4984.06 5015.46
Encroach Node=8348.3
       1 4993.01 5009.05
Encroach Node=7889.1
       1 4984.47 5021.17
Encroach Node=7552.0
       1 4963.65  5021.8
Encroach Node=7080.4
       1    4900    5014
Encroach Node=6578.9
       1    4710    5035
Encroach Node=6318.8
       1    4740    5180
Encroach Node=6204.4
       1    4905    5225
Encroach Node=6159
       1    4905    5225
Encroach Node=6119.8
       1    4905    5225
Encroach Node=6035.2
       1    4905    5280
Encroach Node=5906.9
       1    4965    5269
Encroach Node=5755.1
       1    4945    5405
Encroach Node=5557.0
       1    4935    5475
Encroach Node=5369.4
       1 4981.49    5250
Encroach Node=5352.9
       1 4981.49    5250
Encroach Node=5336.4
       1 4981.49    5250
Encroach Node=5254.6
       1    4975    5250
Encroach Node=5100.0
       1 4984.32    5190
Encroach Node=4853.0
       1    4900    5150
Encroach Node=4725.3
       1    4875    5200
Encroach Node=4707.3
       1    4875    5200
Encroach Node=4689.3
       1    4875    5200
Encroach Node=4620.6
       1    4870    5200
Encroach Node=4393.1
       1    4825    5215
Encroach Node=4179.8
       1    4900    5180
Encroach Node=3911.4
       1    4900    5120
Encroach Node=3251.4
       1    4900    5100
Encroach Node=2784.0
       1    4845    5110
Encroach Node=2705.9
       1    4850    5115
Encroach Node=2674.9
       1    4850    5115
Encroach Node=2643.9
       1    4850    5115
Encroach Node=2552.8
       1    4870    5115
Encroach Node=2377.0
       1    4880    5190
Encroach Node=2236.4
       1  4808.5  5048.5
Encroach Node=2205.4
       1  4808.5  5048.5
Encroach Node=2174.4
       1  4808.5  5048.5
Encroach Node=2094.0
       1    4625 5036.64
Encroach Node=1718.7
       1    4760    5135
Encroach Node=1443.8
       1 4855.22    5261
Encroach Node=755.7
       1    4845    5035
Computation Interval=1HOUR
Output Interval=1HOUR
Run HTab= 0
Run UNet= 0
Run PostProcess= 0
UNET Theta= 1
UNET ZTol= 0.02
UNET ZSATol= 0.1
UNET MxIter= 20
UNET MaxInSteps= 20
UNET DtIC= 0
UNET DtMin= 0
UNET MaxCRTS= 20
UNET WFStab= 2
UNET SFStab= 1
UNET WFX= 1
UNET SFX= 1
UNET Convert EG Bridges=-1
UNET Use Existing IB Tables=-1
Instantaneous Interval=1HOUR
DSS File=dss
Write IC File= 0
Write Velocity= 0
Write Detailed= 0

--- L114-01-00.p02 (plan) ---

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Plan Title=FEMA Effective June 2007
Short Identifier=FEMAeff0607
Geom File=g01
Flow File=f02
Encroach Param=-1 ,0,0, 0

--- L114-01-00.f03 (steady flow) ---

Flow Title=Floodway
Version=Version 3.0.1  Mar 2001
Number of Profiles= 2
Profile Names=1PCT_100yr,1PCTFloodway_100yrFW
River Rch & RM=L114-01-00,L114-01-00_0008 ,13729.4
     280     280
River Rch & RM=L114-01-00,L114-01-00_0008 ,13393.1
     290     290
River Rch & RM=L114-01-00,L114-01-00_0008 ,13117.7
     300     300
River Rch & RM=L114-01-00,L114-01-00_0008 ,12793.9
     310     310
River Rch & RM=L114-01-00,L114-01-00_0008 ,12234.9
     330     330
River Rch & RM=L114-01-00,L114-01-00_0008 ,11671.0
     340     340
River Rch & RM=L114-01-00,L114-01-00_0008 ,11383.1
     350     350
River Rch & RM=L114-01-00,L114-01-00_0008 ,10966.1
     370     370
River Rch & RM=L114-01-00,L114-01-00_0008 ,10393.2
     400     400
River Rch & RM=L114-01-00,L114-01-00_0008 ,9645.0
     420     420
River Rch & RM=L114-01-00,L114-01-00_0008 ,9228.7
     440     440
River Rch & RM=L114-01-00,L114-01-00_0008 ,8694.5
     470     470
River Rch & RM=L114-01-00,L114-01-00_0008 ,7889.1
     500     500
River Rch & RM=L114-01-00,L114-01-00_0008 ,6578.9
    1300    1300
River Rch & RM=L114-01-00,L114-01-00_0008 ,4689.3
    1340    1340
River Rch & RM=L114-01-00,L114-01-00_0008 ,1443.8
    1401    1401
Boundary for River Rch & Prof#=L114-01-00,L114-01-00_0008 , 1
Up Type= 0
Dn Type= 3
Dn Slope=.0012
Boundary for River Rch & Prof#=L114-01-00,L114-01-00_0008 , 2
Up Type= 0
Dn Type= 1
Dn Known WS=185.85
DSS Import GetInterval= 0
DSS Import GetPeak= 0
DSS Import FillOption= 0

--- L114-01-00.f02 (steady flow) ---

Flow Title=FEMA Effective June 2007
Version=Version 3.0.1  Mar 2001
Number of Profiles= 4
Profile Names=10PCT_10yr,2PCT_50yr,1PCT_100yr,0.2PCT_500yr
River Rch & RM=L114-01-00,L114-01-00_0008 ,13729.4
     100     200     280     480
River Rch & RM=L114-01-00,L114-01-00_0008 ,13393.1
     110     200     290     490
River Rch & RM=L114-01-00,L114-01-00_0008 ,13117.7
     110     210     300     510
River Rch & RM=L114-01-00,L114-01-00_0008 ,12793.9
     120     230     310     540
River Rch & RM=L114-01-00,L114-01-00_0008 ,12234.9
     120     240     330     570
River Rch & RM=L114-01-00,L114-01-00_0008 ,11671.0
     130     250     340     590
River Rch & RM=L114-01-00,L114-01-00_0008 ,11383.1
     130     260     350     620
River Rch & RM=L114-01-00,L114-01-00_0008 ,10966.1
     140     280     370     660
River Rch & RM=L114-01-00,L114-01-00_0008 ,10393.2
     150     300     400     710
River Rch & RM=L114-01-00,L114-01-00_0008 ,9645.0
     160     320     420     750
River Rch & RM=L114-01-00,L114-01-00_0008 ,9228.7
     170     340     440     790
River Rch & RM=L114-01-00,L114-01-00_0008 ,8694.5
     180     360     470     840
River Rch & RM=L114-01-00,L114-01-00_0008 ,7889.1
     190     390     500     900
River Rch & RM=L114-01-00,L114-01-00_0008 ,6578.9
     480     950    1300    2300
River Rch & RM=L114-01-00,L114-01-00_0008 ,4689.3
     500     990    1340    2370
River Rch & RM=L114-01-00,L114-01-00_0008 ,1443.8
     536    1066    1401    2498
Boundary for River Rch & Prof#=L114-01-00,L114-01-00_0008 , 1
Up Type= 0
Dn Type= 3
Dn Slope=.0012
Boundary for River Rch & Prof#=L114-01-00,L114-01-00_0008 , 2
Up Type= 0
Dn Type= 3
Dn Slope=.0012
Boundary for River Rch & Prof#=L114-01-00,L114-01-00_0008 , 3
Up Type= 0
Dn Type= 3
Dn Slope=.0012
Boundary for River Rch & Prof#=L114-01-00,L114-01-00_0008 , 4
Up Type= 0
Dn Type= 3
Dn Slope=.0012
DSS Import GetInterval= 0
DSS Import GetPeak= 0
DSS Import FillOption= 0

--- L114-01-00.g01 (geometry) ---

Geom Title=L114-01-00 June 2007
Version=Version 3.0.1  Mar 2001

River Reach=L114-01-00      ,L114-01-00_0008
Reach XY= 30
    2980995.7869   13945918.4125    2981475.3875   13945958.7771
    2981804.8146   13945612.4229    2981922.0021   13945421.0166
    2982089.5369   13944449.2285     2982200.648   13942684.4715
    2982266.1862   13942575.9646    2982370.3528   13942495.2354
    2982601.6896   13942445.3222    2982929.6214   13942110.7552
    2983009.3577   13939976.7179     2983062.309   13939816.9956
    2983231.5799   13939676.3706    2983339.2188   13939644.2526
    2985587.5394   13939598.2394    2985758.7836   13939495.5683
      2986531.75       13938824.      2986596.25       13938793.
      2987027.75       13938801.    2987083.1671   13938522.3322
    2987329.6948    13938503.235    2987467.7157   13938338.3045
    2987670.8407   13938323.5475      2987819.25       13938162.
    2987895.6671   13937902.5406    2988183.8615   13937866.9503
    2988354.8684   13937890.3878    2988406.9518   13937965.9086
    2988607.4726   13937989.3461    2988682.9934   13938091.7767

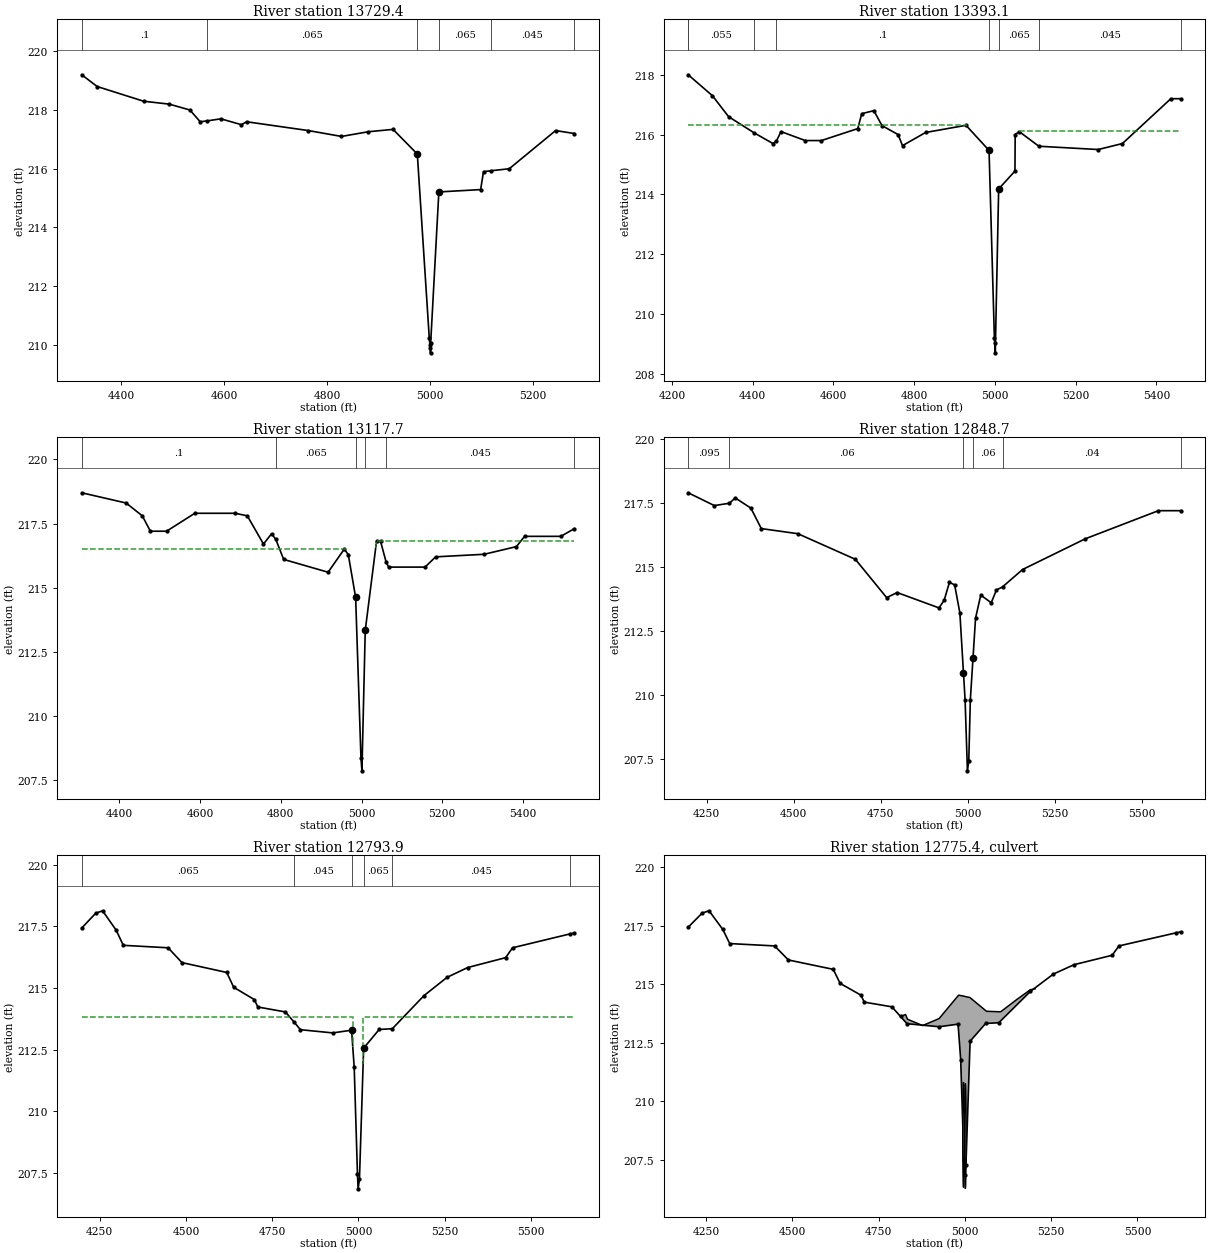
Type RM Length L Ch R = 1 ,13729.4 ,378.4,336.3,241.4
BEGIN DESCRIPTION:
Cross Section XS26
END DESCRIPTION:
XS GIS Cut Line= 2
    2981190.1061   13946607.2913    2981213.6703   13945651.2569
#Sta/Elev= 27
  4323.9   219.2  4353.9   218.8  4443.9   218.3  4493.9   218.2  4533.9     218
  4553.9   217.6  4567.7  217.63  4593.9   217.7  4633.9   217.5  4643.9   217.6
  4763.9   217.3  4828.2   217.1  4880.2  217.26  4928.3  217.34  4975.4   216.5
  4998.6  210.24  4999.9  209.98  5000.7   209.9    5001  209.73  5001.3  210.06
  5017.2  215.21  5098.3  215.29  5103.9   215.9  5117.6  215.93  5153.9     216
  5243.9   217.3  5280.2   217.2
#Mann= 6 ,-1 , 0
  4323.9      .1       0  4567.7    .065       0  4975.4     .05       0
  5017.2    .065       0  5117.6    .045       0  5280.2      .2       0
Bank Sta=4975.4,5017.2
XS Rating Curve= 0
Exp/Cntr=.3,.1

Type RM Length L Ch R = 1 ,13393.1 ,300.4,275.4,249.9
BEGIN DESCRIPTION:
Cross Section XS25
END DESCRIPTION:
XS GIS Cut Line= 3
    2981912.5181   13946578.0044    2981425.7484   13945755.6127
    2981222.3021   13945586.4221
#Sta/Elev= 30
  4240.1     218  4300.1   217.3  4340.1   216.6  4403.2  216.06  4450.1   215.7
  4458.4  215.78  4470.1   216.1  4530.1   215.8  4570.1   215.8  4660.1   216.2
  4670.1   216.7  4700.1   216.8  4720.1   216.3  4760.1     216    4771  215.63
  4828.2  216.07  4928.3  216.31  4985.4  215.47  4998.6  209.21    5001   208.7
  5001.3  209.03  5009.2  214.18  5049.6  214.78  5050.1     216  5060.1   216.1
  5108.8  215.61  5255.8   215.5  5315.8   215.7  5435.8   217.2  5460.4   217.2
#Mann= 8 , 1 , 0
  4240.1      .2       0  4240.1    .055       0  4403.2     .08       0
  4458.4      .1       0  4985.4     .05       0  5009.2    .065       0
  5108.8    .045       0  5460.4      .2       0
#XS Ineff= 2 , 0
         4929.38  216.32 5061.21          216.11
Permanent Ineff=
       F       F
Bank Sta=4985.4,5009.2
XS Rating Curve= 0
Exp/Cntr=.3,.1

Type RM Length L Ch R = 1 ,13117.7 ,357.6,269,198.5
BEGIN DESCRIPTION:
Cross Section XS24
END DESCRIPTION:
XS GIS Cut Line= 3
    2982204.8755   13946194.3459    2981585.0426   13945603.3878
    2981237.6092    13945497.131
#Sta/Elev= 30
  4307.2   218.7  4417.2   218.3  4457.2   217.8  4477.2   217.2  4517.2   217.2
  4587.2   217.9  4687.2   217.9  4717.2   217.8  4757.2   216.7  4777.2   217.1
  4787.8  216.88  4807.2   216.1  4917.2   215.6  4957.2   216.5  4967.2  216.29
  4985.4  214.62  4998.6  208.36    5001  207.85  5009.2  213.33  5037.1   216.8
  5047.2   216.8  5061.2  215.98  5067.2   215.8  5157.2   215.8  5183.6   216.2
  5303.6   216.3  5383.6   216.6  5403.6     217  5493.6     217  5526.9   217.3
#Mann= 6 ,-1 , 0
  4307.2      .1       0  4787.8    .065       0  4985.4     .05       0
  5009.2    .065       0  5061.2    .045       0  5526.9      .2       0
#XS Ineff= 2 , 0
       0    4958   216.5    5035       0   216.8
Permanent Ineff=
       F       F
Bank Sta=4985.4,5009.2
XS Rating Curve= 0
Exp/Cntr=.3,.1

Type RM Length L Ch R = 1 ,12848.7 ,53.6,54.8,54.6
BEGIN DESCRIPTION:
Cross Section XS20.5
END DESCRIPTION:
XS GIS Cut Line= 3
      2982475.75     13945995.13      2982016.59     13945520.79
      2981264.36     13945463.58
#Sta/Elev= 30
  4197.2   217.9  4272.2   217.4  4315.4  217.49  4332.2   217.7  4377.2   217.3
  4407.2   216.5  4512.2   216.3  4677.2   215.3  4767.2   213.8  4797.2     214
  4917.4   213.4  4932.4   213.7  4947.4   214.4  4962.4   214.3  4977.4   213.2
  4987.8  210.84  4992.4   209.8  4999.1  207.03    5003  207.43  5007.4   209.8
  5015.1  211.44  5022.4     213  5037.4   213.9  5067.4   213.6  5082.4   214.1
  5099.8  214.22  5157.4   214.9  5337.4   216.1  5547.4   217.2  5611.8   217.2
#Mann= 6 ,-1 , 0
  4197.2    .095       0  4315.4     .06       0  4987.8     .05       0
  5015.1     .06       0  5099.8     .04       0  5611.8      .2       0
#XS Ineff= 2 , 0
         4948.82  214.38
Permanent Ineff=
       F       F
Bank Sta=4987.8,5015.1
XS Rating Curve= 0
Exp/Cntr=.5,.3

Type RM Length L Ch R = 1 ,12793.9 ,37,37,37
BEGIN DESCRIPTION:
Upstream Section of Bridge/Culvert/Weir
END DESCRIPTION:
XS GIS Cut Line= 3
    2982524.4088   13945930.1581    2982039.2595   13945470.3858
    2981280.8351   13945432.1945
#Sta/Elev= 30
    4198  217.43  4238.4  218.03  4258.4  218.13    4298  217.34  4318.4  216.73
  4448.4  216.63  4488.4  216.03  4618.4  215.63  4638.4  215.03  4698.4  214.53
  4708.4  214.23  4788.4  214.03  4813.4  213.62    4832  213.31  4925.6  213.18
  4980.2  213.29  4987.8  211.78  4997.2  207.47  4999.1  206.86    5003  207.26
  5015.1  212.56  5060.2  213.32  5098.3  213.35    5190  214.69  5256.7  215.43
  5316.7  215.83  5426.7  216.23  5446.7  216.63  5612.6  217.19  5625.8  217.23
#Mann= 6 ,-1 , 0
    4198    .065       0  4813.4    .045       0  4980.2     .05       0
  5015.1    .065       0  5098.3    .045       0  5612.6      .2       0
#XS Ineff= 2 , 0
       0 4983.65  213.82 5013.65       0  213.82
Permanent Ineff=
       F       F
Bank Sta=4980.2,5015.1
XS Rating Curve= 0
Exp/Cntr=.5,.3

Type RM Length L Ch R = 2 ,12775.4 ,,,
BEGIN DESCRIPTION:
Access Road 1000' DS BECKER
Structure ID: L114-01-00-S0-7
END DESCRIPTION:
Bridge Culvert--1,0,-1,-1, 0
Deck Dist Width WeirC Skew NumUp NumDn MinLoCord MaxHiCord MaxSubmerge Is_Ogee
10,17,3,0, 25, 25, , , .95, 0, 1,1,,
  4813.4    4828    4832  4833.7  4877.5  4925.6  4925.9  4980.2  4982.1  4987.8
  4996.1  4997.2  4999.1    5003  5003.9    5014  5015.1  5060.2  5062.7  5098.3
  5103.7  5104.8  5150.2    5190  5203.7
  213.62   213.7  213.56   213.5  213.23  213.53  213.54   214.5  214.53  214.51
  214.49  214.48  214.48  214.46  214.46  214.43  214.42  213.87  213.84  213.82
  213.82  213.83  214.34  214.76   214.8
                                                                                
                                                                                
                                        
  4813.4    4828    4832  4833.7  4877.5  4925.6  4925.9  4980.2  4982.1  4987.8
  4996.1  4997.2  4999.1    5003  5003.9    5014  5015.1  5060.2  5062.7  5098.3
  5103.7  5104.8  5150.2    5190  5203.7
   213.6   213.7  213.56   213.5  213.23  213.53  213.54   214.5  214.53  214.51
  214.49  214.48  214.48  214.46  214.46  214.43  214.42  213.87  213.84  213.82
  213.82  213.83  214.34  214.76 214.796
                                                                                
                                                                                
                                        
BR Coef= 1 , 0 , 0 ,1.25, 0 ,,,.8,-1,2,1,
WSPro=,,,, 1 ,,,, 0 ,,,, 0 ,,,,-1 ,-1 ,-1 , 0 , 0 , 0 , 0 , 0
Culvert=1,4.5,,17,.015,.5,1,1,3,206.32,4995.9,206.17,4995.9,Culvert #1  , 0 ,10
Culvert Bottom n=.015
Culvert=1,4.5,,17,.015,.5,1,1,3,206.26,5001.4,206.08,5001.4,Culvert #2  , 0 ,10
Culvert Bottom n=.015
BC Design=,, 0 ,, 0 ,,,,,,
BC HTab HWMax=218.13

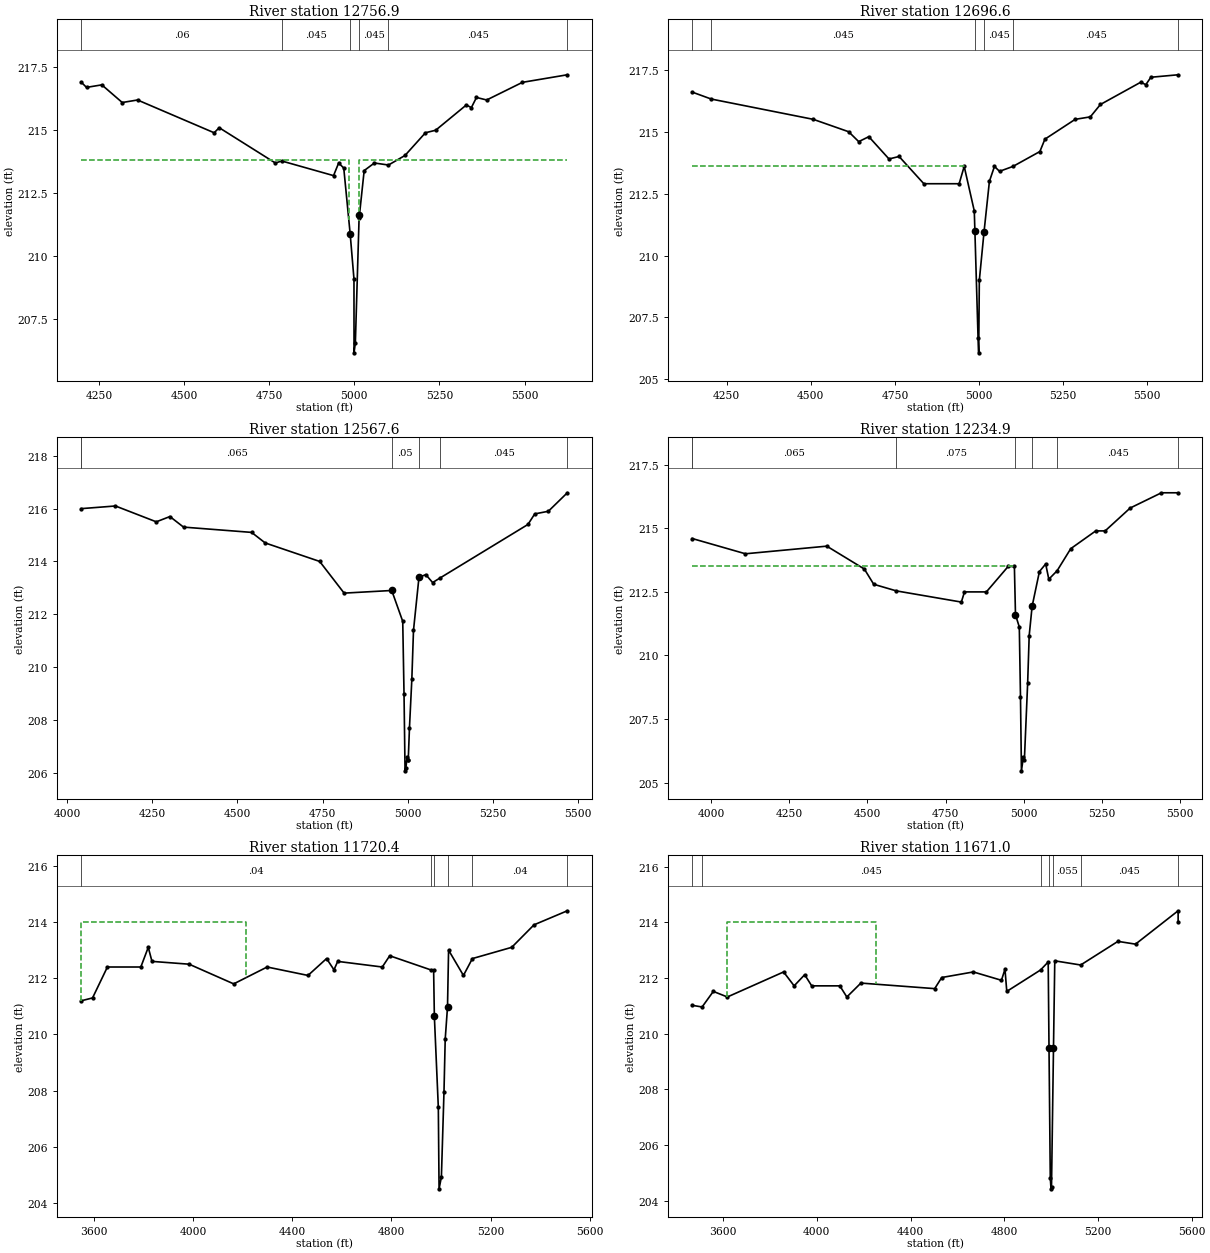
Type RM Length L Ch R = 1 ,12756.9 ,59.6,59.6,59.6
BEGIN DESCRIPTION:
Downstream Section of Bridge/Culvert/Weir
END DESCRIPTION:
XS GIS Cut Line= 3
    2982525.8127    13945892.419    2982083.8519   13945435.2633
    2981292.3638   13945407.3753
#Sta/Elev= 30
    4198   216.9    4213   216.7    4258   216.8    4318   216.1    4363   216.2
    4588   214.9    4603   215.1    4768   213.7  4786.7  213.78  4938.9   213.2
  4953.9   213.7  4968.9   213.5  4987.8  210.88  4998.9   209.1  4999.1  206.17
    5003  206.57  5013.9   211.5  5015.1  211.65  5028.9   213.4  5058.9   213.7
  5100.3  213.62  5148.9     214  5208.9   214.9  5238.9     215  5328.9     216
  5343.9   215.9  5358.9   216.3  5388.9   216.2  5493.9   216.9  5625.8   217.2
#Mann= 6 ,-1 , 0
    4198     .06       0  4786.7    .045       0  4987.8     .05       0
  5015.1    .045       0  5100.3    .045       0  5625.8      .2       0
#XS Ineff= 2 , 0
       0 4983.65  213.82 5013.65       0  213.82
Permanent Ineff=
       F       F
Bank Sta=4987.8,5015.1
XS Rating Curve= 0
Exp/Cntr=.5,.3

Type RM Length L Ch R = 1 ,12696.6 ,109.9,129,144.5
BEGIN DESCRIPTION:
Cross Section XS19.5
END DESCRIPTION:
XS GIS Cut Line= 3
      2982578.21     13945862.31      2982111.46     13945376.59
      2981340.62     13945356.81
#Sta/Elev= 30
  4147.4   216.6  4203.9  216.32  4507.4   215.5  4612.4     215  4642.4   214.6
  4672.4   214.8  4732.4   213.9  4762.4     214    4836   212.9    4941   212.9
    4956   213.6    4986   211.8  4987.8  210.99  4997.2  206.68  4999.1  206.07
    5001     209  5015.1  210.97    5031     213    5046   213.6    5061   213.4
  5101.2   213.6    5181   214.2    5196   214.7    5286   215.5    5331   215.6
    5361   216.1    5481     217    5496   216.9    5511   217.2  5592.1   217.3
#Mann= 6 ,-1 , 0
  4147.4      .2       0  4203.9    .045       0  4987.8     .05       0
  5015.1    .045       0  5101.2    .045       0  5592.1      .2       0
#XS Ineff= 2 , 0
          4956.4   213.6
Permanent Ineff=
       F       F
Bank Sta=4987.8,5015.1
XS Rating Curve= 0
Exp/Cntr=.3,.1

Type RM Length L Ch R = 1 ,12567.6 ,273.4,332.7,336.7
BEGIN DESCRIPTION:
Cross Section XS23
END DESCRIPTION:
XS GIS Cut Line= 3
    2982679.6083   13945830.5896    2982143.2219   13945275.7072
    2981495.9578   13945170.9121
#Sta/Elev= 28
  4041.5     216  4141.5   216.1  4261.5   215.5  4301.5   215.7  4341.5   215.3
  4541.5   215.1  4581.5   214.7  4741.5     214  4813.3   212.8  4953.2   212.9
  4985.5  211.73  4989.3  208.97  4992.3  206.07  4994.6  206.16  4998.4   206.6
  5000.5  206.48  5001.7  206.49  5005.3  207.71  5012.2  209.53  5017.1  211.39
  5033.2   213.4  5053.3   213.5  5073.3   213.2  5094.7  213.37  5353.3   215.4
  5373.3   215.8  5413.3   215.9    5469   216.6
#Mann= 6 , 1 , 0
  4041.5      .2       0  4041.5    .065       0  4953.2     .05       0
  5033.2    .065       0  5094.7    .045       0    5469      .2       0
Bank Sta=4953.2,5033.2
XS Rating Curve= 0
Exp/Cntr=.3,.1

Type RM Length L Ch R = 1 ,12234.9 ,424.2,514.5,494.3
BEGIN DESCRIPTION:
Cross Section XS22
END DESCRIPTION:
XS GIS Cut Line= 3
    2982875.6431   13945539.4197    2982137.0566   13944942.7777
     2981545.182   13944825.6359
#Sta/Elev= 30
  3940.3   214.6  4110.3     214  4370.3   214.3  4490.3   213.4  4520.3   212.8
  4592.5  212.54  4800.3   212.1  4810.3   212.5  4880.3   212.5  4949.8   213.5
  4969.8   213.5  4973.3   211.6  4985.5  211.12  4989.3  208.36  4992.3  205.46
  4998.4  205.99  5001.7  205.88  5012.2  208.92  5017.1  210.78  5026.4  211.93
  5049.8   213.3  5069.8   213.6  5079.8     213  5106.2  213.33  5149.8   214.2
  5229.8   214.9  5259.8   214.9  5339.8   215.8  5439.8   216.4  5493.1   216.4
#Mann= 7 , 1 , 0
  3940.3      .2       0  3940.3    .065       0  4592.5    .075       0
  4973.3     .05       0  5026.4    .075       0  5106.2    .045       0
  5493.1      .2       0
#XS Ineff= 2 , 0
         4968.07  213.53
Permanent Ineff=
       F       F
Bank Sta=4973.3,5026.4
XS Rating Curve= 0
Exp/Cntr=.3,.1

Type RM Length L Ch R = 1 ,11720.4 ,49.4,49.4,49.4
BEGIN DESCRIPTION:
Cross Section XS21.75
END DESCRIPTION:
XS GIS Cut Line= 4
      2983327.74     13945159.03      2982165.87     13944419.34
      2982090.72      13944413.7      2981581.71     13944391.93
#Sta/Elev= 30
    3548   211.2    3593   211.3    3653   212.4    3788   212.4    3818   213.1
    3833   212.6    3983   212.5    4163   211.8    4298   212.4    4463   212.1
    4538   212.7    4568   212.3    4583   212.6    4763   212.4    4793   212.8
  4958.1   212.3  4970.3   212.3  4973.3  210.65  4989.3  207.41  4992.3  204.51
  5001.7  204.93  5012.2  207.97  5017.1  209.83  5026.4  210.98  5030.7     213
  5090.7   212.1  5126.9   212.7  5285.7   213.1  5375.7   213.9  5510.2   214.4
#Mann= 6 ,-1 , 0
    3548     .04       0  4958.1    .055       0  4973.3     .05       0
  5026.4    .055       0  5126.9     .04       0  5510.2      .2       0
#XS Ineff= 2 , 0
       0  4212.6     214               0
Permanent Ineff=
       F       F
Bank Sta=4973.3,5026.4
XS Rating Curve= 0
Exp/Cntr=.5,.3

Type RM Length L Ch R = 1 ,11671.0 ,41,41,41
BEGIN DESCRIPTION:
Upstream Section of Bridge
END DESCRIPTION:
XS GIS Cut Line= 4
    2983468.5996   13945024.0347    2982188.0091    13944370.866
    2982093.6664   13944363.7775    2981552.1715   13944340.6221
#Sta/Elev= 30
  3468.2  211.02  3510.3  210.96  3558.2  211.52  3618.2  211.32  3858.2  212.22
  3903.2  211.72  3948.2  212.12  3978.2  211.72  4098.2  211.72  4128.2  211.32
  4188.2  211.82  4503.2  211.62  4533.2  212.02  4668.2  212.22  4788.2  211.92
  4803.2  212.32  4810.9  211.52  4954.9  212.29  4987.7  212.58 4991.15   209.5
  4996.6  204.82  4999.7  204.42  5001.8  204.48 5010.32   209.5  5015.8  212.62
  5126.3  212.47  5285.4  213.32  5360.4  213.22  5542.3  214.42  5542.4  214.02
#Mann= 7 ,-1 , 0
  3468.2      .1       0  3510.3    .045       0  4954.9    .055       0
 4991.15     .05       0 5010.32    .055       0  5126.3    .045       0
  5542.4      .2       0
#XS Ineff= 3 ,-1
  3614.7  4254.7     214  4254.7  4977.7  211.53  5025.8  5542.4  212.37
Permanent Ineff=
       F       F       F
Bank Sta=4991.15,5010.32
XS Rating Curve= 0
Exp/Cntr=.5,.3

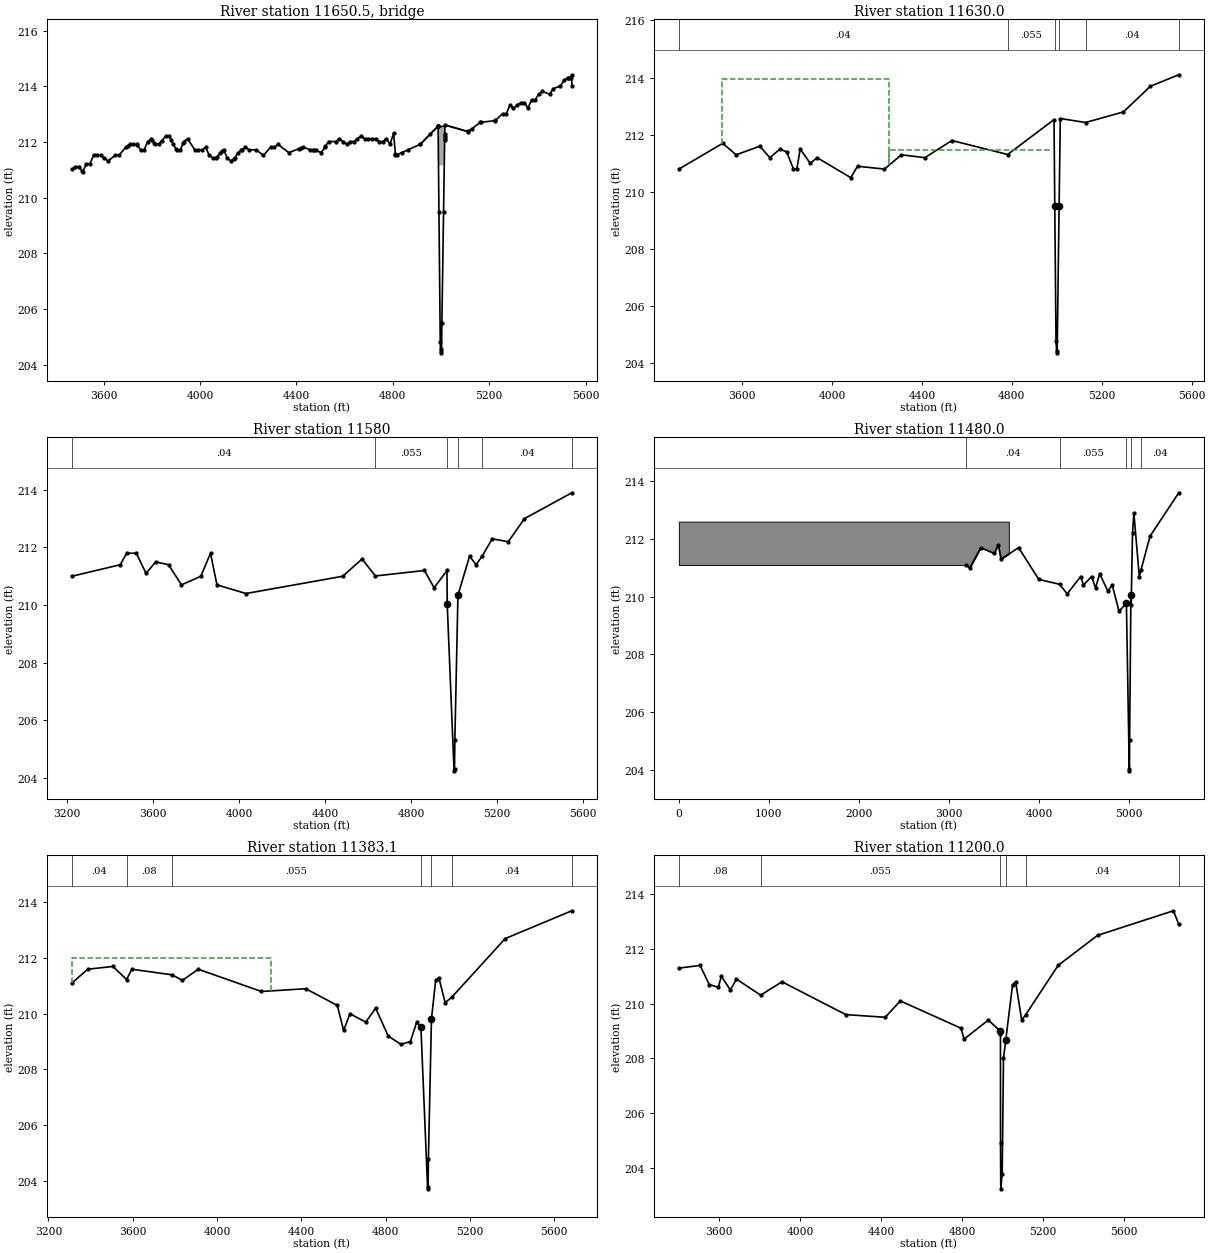
Type RM Length L Ch R = 3 ,11650.5 ,,,
BEGIN DESCRIPTION:
Access Rd 550' US OF BOTKINS
Structure ID: L114-01-00-S4-1
END DESCRIPTION:
Bridge Culvert--1,0,-1,-1, 0
Deck Dist Width WeirC Skew NumUp NumDn MinLoCord MaxHiCord MaxSubmerge Is_Ogee
10,21,2.6,0, 18, 18, , , .95, 0, 1,1,,
  4913.6  4954.9  4985.7 4985.81 4985.93    4986  4987.7  4996.6  4997.7  4999.7
  5001.8  5003.4 5014.87 5014.99  5015.1  5015.2  5015.8    5112
  211.91  212.28  212.54  212.54  212.54  212.54  212.57  212.55  212.56  212.56
  212.56  212.56  212.58  212.58  212.58  212.58  212.61  212.37
                                                  211.17  211.15  211.16  211.16
  211.16  211.16  211.18  211.18  211.18  211.18  211.21
  4913.4  4954.9  4985.7 4985.81 4985.93    4986  4987.7  4996.6  4997.7  4999.7
  5001.8  5003.4 5014.87 5014.99  5015.1  5015.2  5015.8    5112
  211.87  212.28  212.54  212.54  212.54  212.54  212.57  212.55  212.56  212.56
  212.56  212.56  212.58  212.58  212.58  212.58  212.61  212.33
                                                  211.17  211.15  211.16  211.16
  211.16  211.16  211.18  211.18  211.18  211.18  211.21
BR Coef= 1 , 1 , 0 ,1.25, 0 ,,,.8,-1,2,0,
WSPro=,,,, 1 ,,,, 0 ,,,, 0 ,,,,-1 ,-1 ,-1 , 0 , 0 , 0 , 0 , 0
BR U #Sta/Elev= 147
  3468.2  211.02  3483.2  211.12  3498.2  211.12  3510.3  210.96  3513.2  210.92
  3528.2  211.22  3543.2  211.22  3558.2  211.52  3573.2  211.52  3588.2  211.52
  3603.2  211.42  3618.2  211.32  3648.2  211.52  3663.2  211.52  3693.2  211.82
  3700.3  211.87  3708.2  211.92  3723.2  211.92  3738.2  211.92  3740.3  211.89
  3753.2  211.72  3768.2  211.72  3783.2  212.02  3798.2  212.12  3800.3  212.09
  3810.3  211.96  3813.2  211.92  3828.2  211.92  3840.3  212.04  3858.2  212.22
  3873.2  212.22  3880.3  212.08  3888.2  211.92  3900.3  211.76  3903.2  211.72
  3918.2  211.72  3930.3  211.96  3933.2  212.02  3948.2  212.12  3978.2  211.72
  3993.2  211.72  4008.2  211.72  4023.2  211.82  4038.2  211.52  4053.2  211.42
  4068.2  211.42  4070.3  211.45  4083.2  211.62  4090.3  211.67  4098.2  211.72
  4113.2  211.42  4128.2  211.32  4140.3   211.4  4143.2  211.42  4158.2  211.62
  4170.3   211.7  4173.2  211.72  4188.2  211.82  4203.2  211.72  4233.2  211.72
  4263.2  211.52  4293.2  211.82  4308.2  211.82  4323.2  211.92  4368.2  211.62
  4410.3  211.76  4420.3  211.79  4428.2  211.82  4458.2  211.72  4470.3  211.72
  4473.2  211.72  4480.3   211.7  4503.2  211.62  4518.2  211.82  4520.3  211.85
  4533.2  212.02  4563.2  212.02  4578.2  212.12  4593.2  212.02  4608.2  211.92
  4623.2  212.02  4638.2  212.02  4653.2  212.12  4668.2  212.22  4683.2  212.12
  4698.2  212.12  4713.2  212.12  4728.2  212.12  4743.2  212.02  4758.2  212.02
  4773.2  212.12  4788.2  211.92  4803.2  212.32  4810.3  211.58  4810.9  211.52
    4816  211.54    4836  211.62  4861.9  211.72  4913.4  211.92  4913.6  211.92
  4954.9  212.29  4985.7  212.56 4985.81  212.56 4985.93  212.56    4986  212.56
  4987.7  212.58 4991.15   209.5  4996.6  204.82  4997.7  204.57  4999.7  204.42
  5001.8  204.48  5003.4   205.5 5010.32   209.5 5014.87  212.09 5014.99  212.15
  5015.1  212.22  5015.2  212.28  5015.8  212.62    5112  212.38  5113.4  212.39
  5126.3  212.47  5162.7  212.71  5164.8  212.71  5223.1  212.77  5225.4  212.78
  5255.4  213.02  5270.4  213.02  5285.4  213.32  5300.4  213.22  5315.4  213.32
  5330.4  213.42  5345.4  213.42  5360.4  213.22  5375.4  213.52  5390.4  213.52
  5405.4  213.72  5420.4  213.82  5450.4  213.72  5465.4  213.92  5495.4  214.02
  5510.4  214.22  5525.4  214.32    5526  214.32    5536  214.32  5540.4  214.32
  5542.3  214.42  5542.4  214.02
BR U #Mann= 6
  3468.2      .1  3510.3    .045  4954.9    .055 4991.15     .04 5010.32    .055
  5126.3    .045
BR D #Sta/Elev= 117
  3318.2   210.8  3348.2   210.9  3363.2     211  3378.2   211.2  3393.2   211.3
  3408.2   211.4  3423.2   211.3  3453.2   211.6  3468.2   211.6  3483.2   211.5
  3498.2   211.5  3513.2   211.7  3528.2   211.4  3573.2   211.3  3588.2   211.5
  3618.2   211.5  3633.2   211.4  3648.2   211.4  3663.2   211.6  3678.2   211.6
  3693.2   211.4  3708.2   211.2  3723.2   211.2  3738.2   211.4  3753.2   211.4
  3768.2   211.5  3783.2   211.4  3798.2   211.4  3813.2   210.9  3828.2   210.8
  3843.2   210.8  3858.2   211.5  3873.2   211.3  3888.2   211.1  3903.2     211
  3918.2   211.1  3933.2   211.2  3948.2     211  3993.2   210.9  4008.2   210.9
  4023.2   210.9  4038.2   210.8  4053.2   210.7  4068.2   210.7  4083.2   210.5
  4098.2   210.8  4113.2   210.9  4128.2   210.9  4158.2   210.9  4173.2     211
  4203.2     211  4218.2   210.9  4233.2   210.8  4248.2   210.9  4263.2   211.1
  4278.2   211.2  4308.2   211.3  4323.2   211.3  4338.2   211.4  4383.2   211.3
  4398.2   211.2  4413.2   211.2  4428.2   211.3  4443.2   211.3  4458.2   211.3
  4473.2   211.4  4488.2   211.5  4518.2   211.6  4533.2   211.8  4548.2   211.7
  4563.2   211.7  4593.2   211.8  4608.2   211.7  4623.2   211.6  4638.2   211.6
  4653.2   211.5  4668.2   211.6  4683.2   211.5  4698.2   211.6  4728.2   211.5
  4743.2   211.5  4758.2   211.5  4773.2   211.2  4781.2  211.31  4788.2   211.4
  4803.2   211.6  4810.9  211.47  4913.4  211.87  4987.7  212.53 4991.07   209.5
  4996.6  204.77  4997.7  204.52  4999.7  204.37  5001.8  204.43  5003.4  205.45
  5010.3   209.5  5015.8  212.57    5112  212.33    5128  212.43  5162.7  212.66
  5223.1  212.72  5225.4  212.73  5251.7   212.7  5281.7   212.9  5296.7   212.8
  5311.7   212.9  5326.7     213  5371.7   213.3  5386.7   213.5  5401.7   213.6
  5416.7   213.7  5431.7   213.7  5446.7   213.7  5491.7   213.9  5506.7     214
  5536.7   214.2    5543   214.1
BR D #Mann= 5
  3318.2     .04  4781.2    .055 4991.07     .04  5010.3    .055    5128     .04
BC Design=,, 0 ,, 0 ,,,,,,
BC HTab HWMax=214.22

Type RM Length L Ch R = 1 ,11630.0 ,50,50,50
BEGIN DESCRIPTION:
Downstream Section of Bridge
END DESCRIPTION:
XS GIS Cut Line= 3
       2983621.2     13945006.43      2982283.01     13944332.15
       2981557.4     13944300.14
#Sta/Elev= 30
  3318.2   210.8  3513.2   211.7  3573.2   211.3  3678.2   211.6  3723.2   211.2
  3768.2   211.5  3798.2   211.4  3828.2   210.8  3843.2   210.8  3858.2   211.5
  3903.2     211  3933.2   211.2  4083.2   210.5  4113.2   210.9  4233.2   210.8
  4308.2   211.3  4413.2   211.2  4533.2   211.8  4781.2  211.31  4987.7  212.53
 4991.07   209.5  4996.6  204.77  4999.7  204.37  5001.8  204.43  5010.3   209.5
  5015.8  212.57    5128  212.43  5296.7   212.8  5416.7   213.7    5543   214.1
#Mann= 6 ,-1 , 0
  3318.2     .04       0  4781.2    .055       0 4991.07     .05       0
  5010.3    .055       0    5128     .04       0    5543      .2       0
#XS Ineff= 3 ,-1
  3510.9  4254.7  213.95  4254.7  4977.7  211.48  5025.8  5542.4  212.32
Permanent Ineff=
       F       F       F
Bank Sta=4991.07,5010.3
XS Rating Curve= 0
Exp/Cntr=.5,.3

Type RM Length L Ch R = 1 ,11580   ,100,100,100
BEGIN DESCRIPTION:
Cross Section XS21.5
END DESCRIPTION:
XS GIS Cut Line= 3
      2983726.84     13944971.21      2982304.34     13944283.04
       2981559.6     13944250.18
#Sta/Elev= 30
  3221.7     211  3446.7   211.4  3476.7   211.8  3521.7   211.8  3566.7   211.1
  3611.7   211.5  3671.7   211.4  3731.7   210.7  3821.7     211  3866.7   211.8
  3896.7   210.7  4031.7   210.4  4481.7     211  4571.7   211.6  4633.6  211.01
  4861.9   211.2  4906.9   210.6  4966.9   211.2  4967.8  210.04  4999.7  204.24
  5001.8   204.3  5003.4  205.32  5017.8  210.34  5071.9   211.7  5101.9   211.4
  5130.6   211.7  5176.9   212.3  5251.9   212.2  5326.9     213  5547.4   213.9
#Mann= 6 ,-1 , 0
  3221.7     .04       0  4633.6    .055       0  4967.8     .05       0
  5017.8    .055       0  5130.6     .04       0  5547.4      .2       0
Bank Sta=4967.8,5017.8
XS Rating Curve= 0
Exp/Cntr=.3,.1

Type RM Length L Ch R = 1 ,11480.0 ,103.3,96.9,95.4
BEGIN DESCRIPTION:
Cross Section XS21.25
END DESCRIPTION:
XS GIS Cut Line= 3
      2983820.75     13944754.05      2982346.98     13944184.82
      2981564.01     13944150.28
#Sta/Elev= 30
  3185.7   211.1  3230.7     211  3350.7   211.7  3500.7   211.5  3545.7   211.8
  3575.7   211.3  3770.7   211.7  3995.7   210.6  4225.5  210.43  4310.7   210.1
  4460.7   210.7  4490.7   210.4  4580.7   210.7  4625.7   210.3  4670.7   210.8
  4760.7   210.2  4810.6   210.4  4885.6   209.5  4967.8  209.77  4999.7  203.97
  5001.8  204.03  5003.4  205.05  5017.8  210.07  5020.6   209.7  5035.6   212.2
  5050.6   212.9  5110.6   210.7  5128.8  210.92  5230.6   212.1  5549.3   213.6
#Mann= 5 ,-1 , 0
  3185.7     .04       0  4225.5    .055       0  4967.8     .05       0
  5017.8    .055       0  5128.8     .04       0
#Block Obstruct= 2 , 0
       0  3662.5   212.6               0
Bank Sta=4967.8,5017.8
XS Rating Curve= 0
Exp/Cntr=.3,.1

Type RM Length L Ch R = 1 ,11383.1 ,202.9,183.1,180.8
BEGIN DESCRIPTION:
Cross Section XS21
END DESCRIPTION:
XS GIS Cut Line= 3
       2983773.8     13944337.34      2982368.49     13944090.18
       2981423.1     13944049.41
#Sta/Elev= 30
  3310.9   211.1  3385.9   211.6  3505.9   211.7  3570.7  211.23  3595.9   211.6
  3785.7   211.4  3835.9   211.2  3910.9   211.6  4210.9   210.8  4420.9   210.9
  4570.9   210.3  4600.9   209.4  4630.9     210  4705.9   209.7  4752.8   210.2
  4812.8   209.2  4872.8   208.9  4917.8     209  4947.8   209.7  4967.8  209.51
  4999.7  203.71  5001.8  203.77  5003.4  204.79  5017.8  209.81  5037.8   211.2
  5052.8   211.3  5082.8   210.4  5114.9   210.6  5367.8   212.7    5684   213.7
#Mann= 7 ,-1 , 0
  3310.9     .04       0  3570.7     .08       0  3785.7    .055       0
  4967.8     .05       0  5017.8    .055       0  5114.9     .04       0
    5684      .2       0
#XS Ineff= 2 , 0
       0    4254     212               0
Permanent Ineff=
       F       F
Bank Sta=4967.8,5017.8
XS Rating Curve= 0
Exp/Cntr=.3,.1

Type RM Length L Ch R = 1 ,11200.0 ,81.9,86.7,87
BEGIN DESCRIPTION:
Cross Section XS18.5
END DESCRIPTION:
XS GIS Cut Line= 2
      2983720.04     13943938.31      2981249.11      13943877.3
#Sta/Elev= 30
  3400.1   211.3  3505.1   211.4  3550.1   210.7  3595.1   210.6  3610.1     211
  3655.1   210.5  3685.1   210.9  3804.4  210.31  3910.1   210.8  4225.1   209.6
  4420.1   209.5  4495.1   210.1  4795.1   209.1  4810.1   208.7  4930.1   209.4
  4986.1  209.01  4990.1   208.9  4990.4   204.9  4991.6  203.22  4998.7  203.78
  5005.1     208  5016.1  208.66  5050.1   210.7  5065.1   210.8  5095.1   209.4
  5114.5  209.59  5275.1   211.4  5470.1   212.5  5845.1   213.4  5871.8   212.9
#Mann= 6 ,-1 , 0
  3400.1     .08       0  3804.4    .055       0  4986.1     .05       0
  5016.1    .055       0  5114.5     .04       0  5871.8      .2       0
Bank Sta=4986.1,5016.1
XS Rating Curve= 0
Exp/Cntr=.5,.3