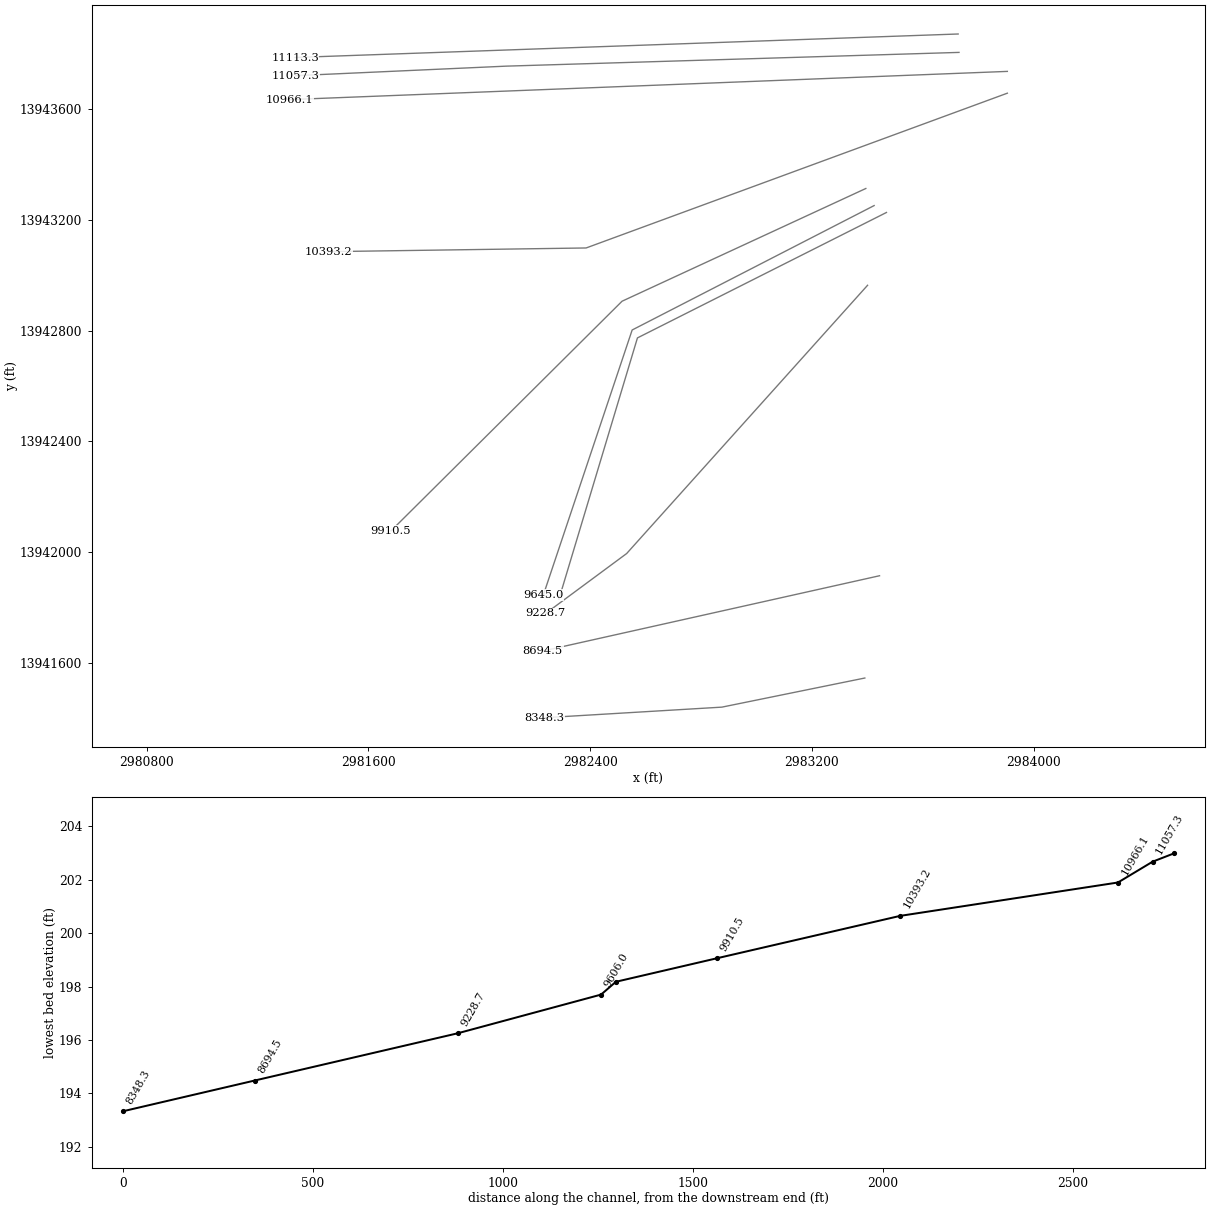
HEC-RAS study L114-01-00.PRJ: L114-01-00

--- L114-01-00.g01 (geometry) --- (continued)

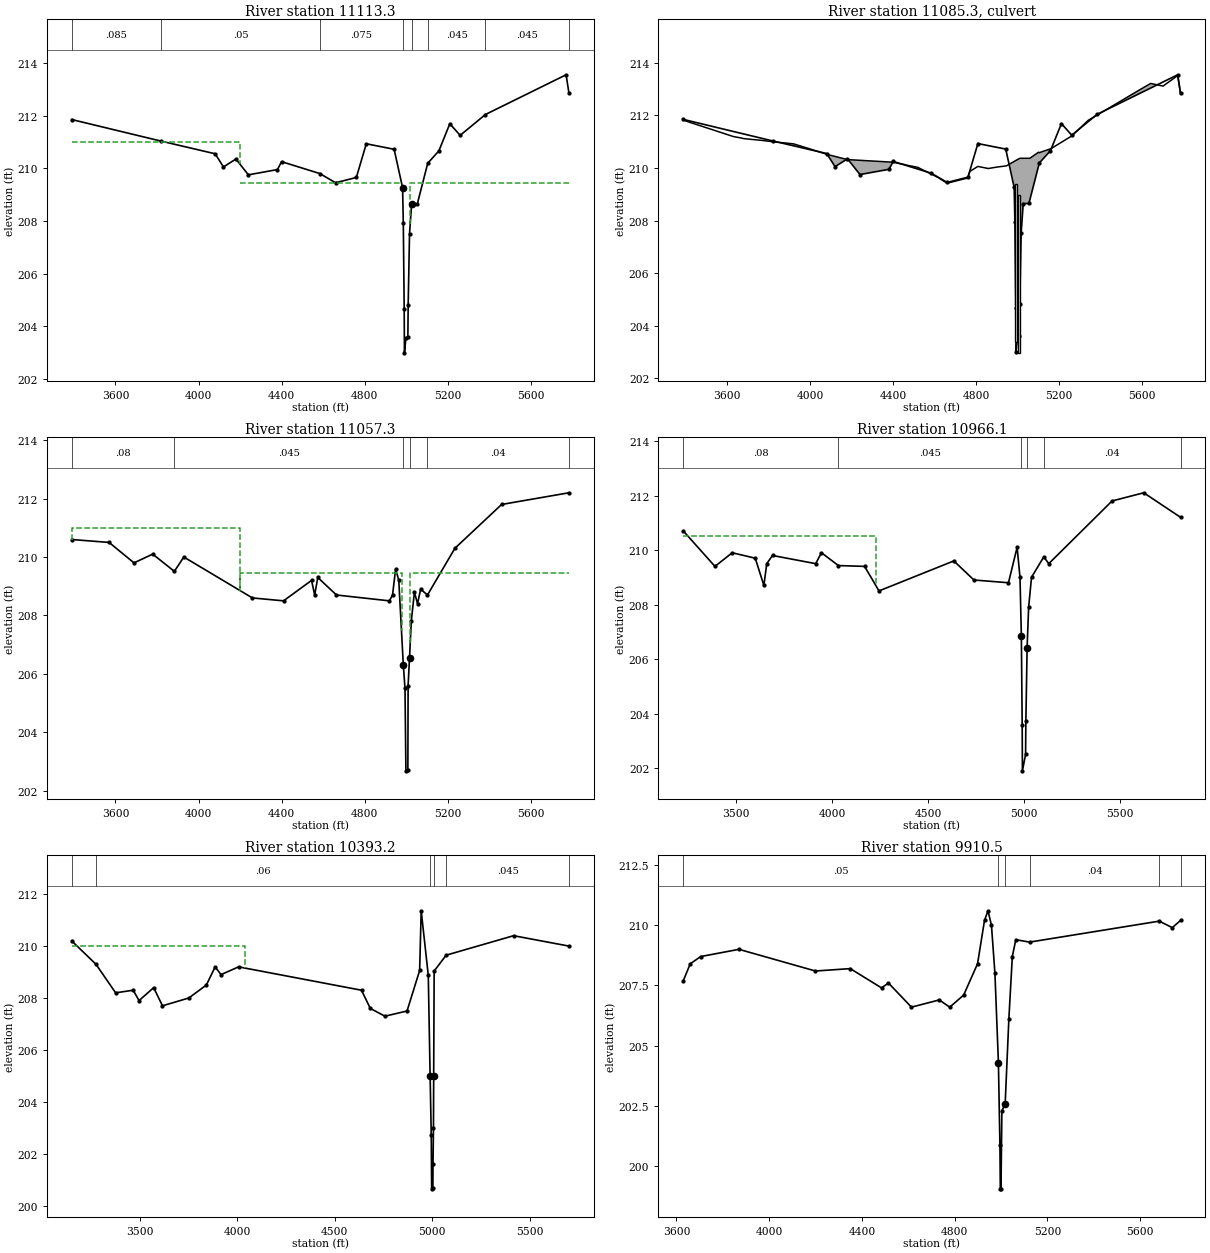
Type RM Length L Ch R = 1 ,11113.3 ,56,56,56
BEGIN DESCRIPTION:
Upstream Section of Bridge
END DESCRIPTION:
XS GIS Cut Line= 2
    2983727.8586   13943870.4301     2981334.674   13943785.5904
#Sta/Elev= 30
  3389.3  211.85    3820  211.03    4080  210.55    4120  210.05    4180  210.35
    4240  209.75    4380  209.95    4400  210.25  4583.7   209.8    4660  209.45
    4760  209.65  4807.9  210.93    4942  210.72  4982.7  209.26  4986.1  207.93
  4990.4  204.67  4991.6  202.99  4998.7  203.55  5008.1  203.59  5009.6  204.81
  5016.1  207.51  5026.2  208.64  5053.7  208.65  5103.8  210.19  5157.5  210.66
  5210.1  211.69    5260  211.25  5381.4  212.04  5770.1  213.55  5783.9  212.85
#Mann= 8 ,-1 , 0
  3389.3    .085       0    3820     .05       0  4583.7    .075       0
  4982.7     .05       0  5026.2    .075       0  5103.8    .045       0
  5381.4    .045       0  5783.9      .2       0
#XS Ineff= 3 ,-1
  3389.3    4200     211    4200  4977.5  209.45  5019.5  5783.9  209.45
Permanent Ineff=
       F       F       F
Bank Sta=4982.7,5026.2
XS Rating Curve= 0
Exp/Cntr=.5,.3

Type RM Length L Ch R = 2 ,11085.3 ,,,
BEGIN DESCRIPTION:
BOTKINS ROAD
Structure ID: L114-01-00-S4
END DESCRIPTION:
Bridge Culvert--1,0,-1,-1, 0
Deck Dist Width WeirC Skew NumUp NumDn MinLoCord MaxHiCord MaxSubmerge Is_Ogee
10,36,3,0, 57, 57, , , .95, 0, 1,1,,
  3389.3  3629.3  3669.3    3680  3729.3  3769.3    3820    3920  3969.3  3989.3
  4009.3  4049.3  4069.3    4080    4180    4400  4429.3  4449.3    4460  4469.3
  4509.3    4520  4529.3  4549.3  4583.7    4620  4629.3    4660  4669.3  4689.3
  4709.3    4760  4769.3  4807.9  4857.9    4904    4945    4987    5010    5058
    5100  5103.8  5106.2  5109.3  5157.5  5160.6    5260    5340  5381.4  5444.9
  5544.9  5604.9    5640    5700  5704.9  5770.1  5783.9
  211.82   211.2  211.14  211.12  211.08  211.05     211  210.92   210.8  210.75
   210.7   210.6  210.55  210.52  210.32  210.22  210.17  210.14  210.12   210.1
  210.04  210.02  209.98   209.9  209.77  209.62  209.57  209.42  209.44  209.48
  209.52  209.62  209.87  210.06  209.98  210.04  210.08  210.27  210.37  210.37
   210.6  210.58  210.59   210.6  210.73  210.74  211.22  211.82  212.01  212.31
  212.78  213.06  213.22  213.12  213.15  213.52  212.82
                                                                                
                                                                                
                                                                                
                                                                                
                                                                                
                                                        
  3389.3  3629.3  3669.3    3680  3729.3  3769.3    3820    3920  3969.3  3989.3
  4009.3  4049.3  4069.3    4080    4180    4400  4429.3  4449.3    4460  4469.3
  4509.3    4520  4529.3  4549.3  4583.7    4620  4629.3    4660  4669.3  4689.3
  4709.3    4760  4769.3  4807.9  4857.9    4904    4945    4987    5010    5058
    5100  5103.8  5106.2  5109.3  5157.5  5160.6    5260    5340  5381.4  5444.9
  5544.9  5604.9    5640    5700  5704.9  5770.1  5783.9
  211.82   211.2  211.14  211.12  211.08  211.05     211  210.92   210.8  210.75
   210.7   210.6  210.55  210.52  210.32  210.22  210.17  210.14  210.12   210.1
  210.04  210.02  209.98   209.9  209.77  209.62  209.57  209.42  209.44  209.48
  209.52  209.62  209.87  210.06  209.98  210.04  210.08  210.27  210.37  210.37
   210.6  210.58  210.59   210.6  210.73  210.74  211.22  211.82  212.01  212.31
  212.78  213.06  213.22  213.12  213.15  213.52  212.82
                                                                                
                                                                                
                                                                                
                                                                                
                                                                                
                                                        
BR Coef= 1 , 1 , 1 ,1.25, 0 ,,,.8,0,2,0,
WSPro=,,,, 1 ,,,, 0 ,,,, 0 ,,,,-1 ,-1 ,-1 , 0 , 0 , 0 , 0 , 0
Culvert=2,6,10,36,.015,.5,1,8,1,203.38,4992.5,201.78,4992.5,Culvert #1  , 0 ,10
Culvert Bottom n=.015
Culvert=2,6,10,36,.015,.5,1,8,1,202.96,5004.5,201.46,5004.5,Culvert #2  , 0 ,10
Culvert Bottom n=.015
BC Design=,, 0 ,, 0 ,,,,,,
BC HTab HWMax=213.55

Type RM Length L Ch R = 1 ,11057.3 ,86.7,91.2,90.6
BEGIN DESCRIPTION:
Downstream Section of Bridge
END DESCRIPTION:
XS GIS Cut Line= 3
    2983730.8959    13943804.003     2982096.374   13943754.3806
    2981337.8054   13943720.0304
#Sta/Elev= 30
  3389.3   210.6  3569.3   210.5  3689.3   209.8  3779.3   210.1  3883.5  209.51
  3929.3     210  4259.3   208.6  4409.3   208.5  4544.3   209.2  4559.3   208.7
  4574.3   209.3  4664.3   208.7  4919.3   208.5  4934.3   208.7  4949.3   209.6
  4964.3   209.2  4986.1  206.32  4994.3   205.5  4998.7  202.68  5008.1  202.72
  5009.3   205.6  5016.1  206.55  5024.6   207.8  5039.6   208.8  5054.6   208.4
  5069.6   208.9  5102.5   208.7  5234.6   210.3  5459.6   211.8  5783.9   212.2
#Mann= 6 ,-1 , 0
  3389.3     .08       0  3883.5    .045       0  4986.1     .05       0
  5016.1    .045       0  5102.5     .04       0  5783.9      .2       0
#XS Ineff= 3 ,-1
  3389.3    4200     211    4200  4977.5  209.45  5019.5  5783.9  209.45
Permanent Ineff=
       F       F       F
Bank Sta=4986.1,5016.1
XS Rating Curve= 0
Exp/Cntr=.5,.3

Type RM Length L Ch R = 1 ,10966.1 ,514.6,572.9,571.5
BEGIN DESCRIPTION:
Cross Section XS20
END DESCRIPTION:
XS GIS Cut Line= 2
    2983905.3085   13943735.4712     2981315.426   13943633.7258
#Sta/Elev= 30
    3224   210.7    3389   209.4    3479   209.9    3599   209.7    3644   208.7
    3659   209.5    3689   209.8    3914   209.5    3944   209.9  4032.5  209.43
    4169   209.4    4244   208.5    4634   209.6    4739   208.9    4919   208.8
    4964   210.1    4979     209  4986.1  206.84  4990.4  203.58  4991.6   201.9
  5008.1   202.5  5009.6  203.72  5016.1  206.42    5024   207.9    5039     209
  5103.1  209.75    5129   209.5    5459   211.8    5624   212.1  5815.9   211.2
#Mann= 6 ,-1 , 0
    3224     .08       0  4032.5    .045       0  4986.1     .05       0
  5016.1     .05       0  5103.1     .04       0  5815.9      .2       0
#XS Ineff= 2 , 0
       0    4230   210.5               0
Permanent Ineff=
       F       F
Bank Sta=4986.1,5016.1
XS Rating Curve= 0
Exp/Cntr=.3,.1

Type RM Length L Ch R = 1 ,10393.2 ,232.7,482.7,510.1
BEGIN DESCRIPTION:
Cross Section XS19
END DESCRIPTION:
XS GIS Cut Line= 3
    2983905.3085   13943656.8497    2982385.3346   13943098.3293
    2981456.6753   13943084.9993
#Sta/Elev= 30
  3151.9   210.2  3276.2   209.3  3376.9   208.2  3466.9   208.3  3496.9   207.9
  3571.9   208.4  3616.9   207.7  3751.9     208  3841.9   208.5  3886.9   209.2
  3916.9   208.9  4006.9   209.2  4636.9   208.3  4681.9   207.6  4756.9   207.3
  4870.2   207.5  4934.8  209.06  4942.8  211.36  4979.1  208.87 4988.51     205
  4994.3  202.73  4996.3  200.65  5002.7   200.7  5003.3   201.6  5005.7     203
 5006.72     205  5009.2  209.04  5070.8  209.65  5416.2   210.4    5700     210
#Mann= 6 ,-1 , 0
  3151.9    .045       0  3276.2     .06       0 4988.51     .05       0
 5006.72     .06       0  5070.8    .045       0    5700      .2       0
#XS Ineff= 2 , 0
       0  4041.9     210               0
Permanent Ineff=
       F       F
Bank Sta=4988.51,5006.72
XS Rating Curve= 0
Exp/Cntr=.3,.1

Type RM Length L Ch R = 1 ,9910.5  ,111.9,265.5,289.3
BEGIN DESCRIPTION:
Cross Section XS17.5
END DESCRIPTION:
XS GIS Cut Line= 3
      2983394.65     13943312.95      2982515.08     13942906.21
      2981681.27     13942077.48
#Sta/Elev= 30
  3629.9   207.7  3659.9   208.4  3704.9   208.7  3869.9     209  4199.9   208.1
  4349.9   208.2  4484.9   207.4  4514.9   207.6    4614   206.6    4734   206.9
    4779   206.6    4839   207.1    4899   208.4    4929   210.2    4944   210.6
    4959     210    4974     208    4989   204.3  4995.5  200.86  4997.2  199.06
  5000.1  199.07    5004   202.3  5018.1  202.58    5034   206.1    5049   208.7
    5064   209.4  5123.6   209.3  5682.7  210.17    5739   209.9  5774.6   210.2
#Mann= 6 ,-1 , 0
  3629.9     .05       0    4989     .05       0  5018.1     .05       0
  5123.6     .04       0  5682.7     .08       0  5774.6      .2       0
Bank Sta=4989,5018.1
XS Rating Curve= 0
Exp/Cntr=.5,.3

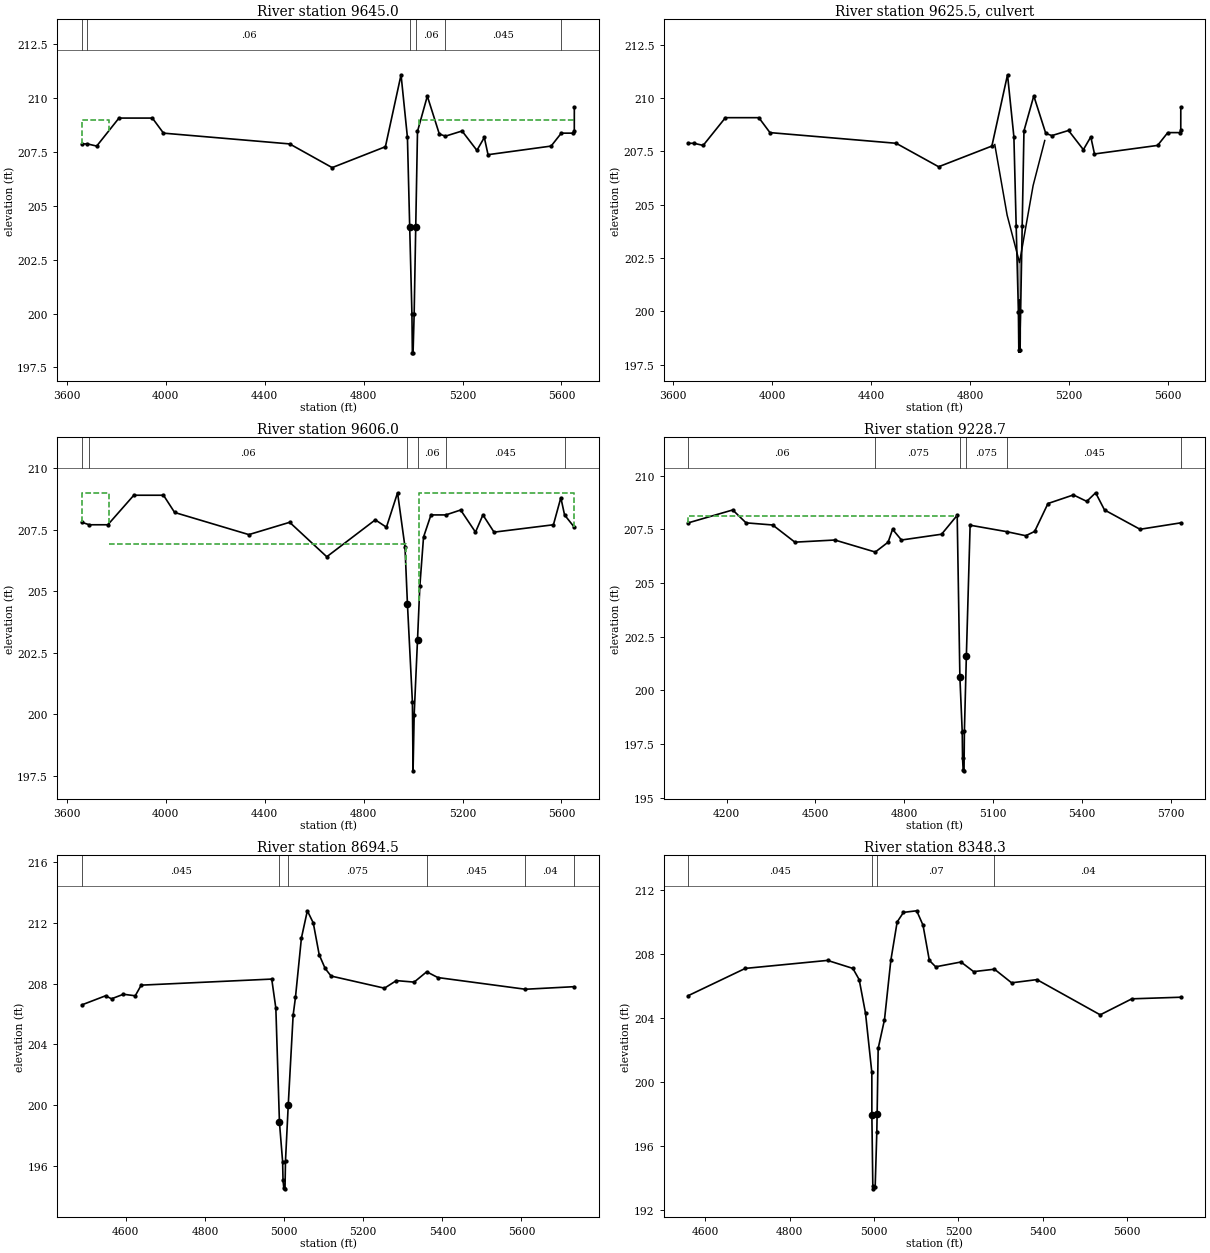
Type RM Length L Ch R = 1 ,9645.0  ,39,39,39
BEGIN DESCRIPTION:
Upstream Section of Bridge
END DESCRIPTION:
XS GIS Cut Line= 3
    2983424.6224   13943251.2614    2982551.4684   13942802.3549
    2982230.9306   13941845.8296
#Sta/Elev= 30
  3661.3  207.88  3683.9  207.88  3721.3  207.78  3811.3  209.08  3946.3  209.08
  3991.3  208.38  4501.3  207.88  4673.1  206.78  4888.3  207.75  4951.5  211.09
  4977.3  208.18 4986.53     204  4995.5  199.98  4997.2  198.18  5000.1  198.19
  5004.5     200 5010.82     204    5018  208.46  5057.7   210.1  5106.2  208.34
  5130.9  208.24  5198.1  208.48  5258.1  207.58  5288.1  208.18  5303.1  207.38
  5558.1  207.78  5599.3  208.38  5648.1  208.38  5651.8  208.48  5651.9  209.58
#Mann= 6 ,-1 , 0
  3661.3      .2       0  3683.9     .06       0 4986.53     .05       0
 5010.82     .06       0  5130.9    .045       0  5599.3      .2       0
#XS Ineff= 3 ,-1
  3661.3  3771.3     209  3771.3  4970.6   206.9 5024.77  5651.9     209
Permanent Ineff=
       F       F       F
Bank Sta=4986.53,5010.82
XS Rating Curve= 0
Exp/Cntr=.5,.3

Type RM Length L Ch R = 2 ,9625.5  ,,,
BEGIN DESCRIPTION:
Access Rd 1450' DS BOTKINS
Structure ID: L114-01-00-S06
END DESCRIPTION:
Bridge Culvert--1,0,-1,-1, 0
Deck Dist Width WeirC Skew NumUp NumDn MinLoCord MaxHiCord MaxSubmerge Is_Ogee
10,19,3,0, 5, 5, , , .95, 0, 1,1,,
    4900    4950    5000    5055    5102
  207.82  204.51  202.29   205.9  208.01
                                        
    4900    4950    5000    5055    5102
 207.752  204.51  202.29   205.9  208.01
                                        
BR Coef= 1 , 0 , 0 ,1.25, 0 ,,,.8,-1,2,0,
WSPro=,,,, 1 ,,,, 0 ,,,, 0 ,,,,-1 ,-1 ,-1 , 0 , 0 , 0 , 0 , 0
Culvert=1,2.5,,19,.015,.5,1,1,3,198.06,4998.2,197.91,4998.2,Culvert #1  , 0 ,10
Culvert Bottom n=.015
Culvert=1,2.5,,19,.015,.5,1,1,3,198.07,5002.4,197.68,5002.4,Culvert #2  , 0 ,10
Culvert Bottom n=.015
BC Design=,, 0 ,, 0 ,,,,,,
BC HTab HWMax=210.26

Type RM Length L Ch R = 1 ,9606.0  ,535.7,377.3,364.5
BEGIN DESCRIPTION:
Downstream Section of Bridge
END DESCRIPTION:
XS GIS Cut Line= 3
    2983469.0787   13943226.3905    2982570.5349   13942773.7552
    2982287.1573   13941830.8807
#Sta/Elev= 30
  3661.3   207.8  3691.3   207.7  3766.3   207.7  3871.3   208.9  3991.3   208.9
  4036.3   208.2  4336.3   207.3  4501.3   207.8  4651.3   206.4  4847.4   207.9
  4892.4   207.6  4937.4     209  4967.4   206.8  4977.3  204.49  4997.4   200.5
  5000.1   197.7  5004.5  199.97  5018.1  203.03  5027.4   205.2  5042.4   207.2
  5072.4   208.1  5132.4   208.1  5192.4   208.3  5252.4   207.4  5282.4   208.1
  5327.4   207.4  5567.4   207.7  5597.4   208.8  5612.4   208.1  5651.9   207.6
#Mann= 6 ,-1 , 0
  3661.3      .2       0  3691.3     .06       0  4977.3     .05       0
  5018.1     .06       0  5132.4    .045       0  5612.4      .2       0
#XS Ineff= 3 ,-1
  3661.3  3771.3     209  3771.3  4970.6   206.9 5024.77  5651.9     209
Permanent Ineff=
       F       F       F
Bank Sta=4977.3,5018.1
XS Rating Curve= 0
Exp/Cntr=.5,.3

Type RM Length L Ch R = 1 ,9228.7  ,553,534.2,510.8
BEGIN DESCRIPTION:
Cross Section XS18
END DESCRIPTION:
XS GIS Cut Line= 3
    2983400.9555    13942963.697    2982531.6397   13941995.7354
     2982240.037     13941780.09
#Sta/Elev= 30
  4070.9   207.8  4220.9   208.4  4265.9   207.8  4355.9   207.7  4430.9   206.9
  4565.9     207  4702.5  206.44  4745.9   206.9  4760.9   207.5  4790.9     207
  4926.5  207.27  4979.2  208.15  4988.3  200.63  4996.3  198.04  4997.3  196.85
  4999.4  196.28  5002.3  196.25  5003.6  198.11 5010.16  201.58  5022.9  207.69
  5146.1  207.39  5210.9   207.2  5240.9   207.4  5285.9   208.7  5371.9   209.1
  5416.9   208.8  5446.9   209.2  5476.9   208.4  5596.9   207.5  5734.6   207.8
#Mann= 6 ,-1 , 0
  4070.9     .06       0  4702.5    .075       0  4988.3     .05       0
 5010.16    .075       0  5146.1    .045       0  5734.6      .2       0
#XS Ineff= 2 , 0
       0 4978.73  208.14               0
Permanent Ineff=
       F       F
Bank Sta=4988.3,5010.16
XS Rating Curve= 0
Exp/Cntr=.3,.1

Type RM Length L Ch R = 1 ,8694.5  ,347.3,346.2,345.6
BEGIN DESCRIPTION:
Cross Section XS17
END DESCRIPTION:
XS GIS Cut Line= 2
     2983444.113   13941915.5857    2982229.2431   13941643.9519
#Sta/Elev= 30
  4488.8   206.6  4548.8   207.2  4563.8     207  4593.8   207.3  4623.8   207.2
  4638.8   207.9  4968.8   208.3  4979.2  206.38  4988.3  198.86  4996.3  196.27
  4997.3  195.08  4999.4  194.51  5002.3  194.48  5003.6  196.34  5010.5  199.99
  5022.9  205.92  5028.8   207.1  5043.8     211  5058.8   212.8  5073.8     212
  5088.8   209.9  5103.8     209  5118.8   208.5  5253.8   207.7  5283.8   208.2
  5328.8   208.1  5360.5  208.78  5388.8   208.4    5610  207.63  5733.7   207.8
#Mann= 6 ,-1 , 0
  4488.8    .045       0  4988.3     .05       0  5010.5    .075       0
  5360.5    .045       0    5610     .04       0  5733.7      .2       0
Bank Sta=4988.3,5010.5
XS Rating Curve= 0
Exp/Cntr=.3,.1

Type RM Length L Ch R = 1 ,8348.3  ,460.6,459.2,453.4
BEGIN DESCRIPTION:
Cross Section XS16.5
END DESCRIPTION:
XS GIS Cut Line= 3
      2983391.05     13941546.52      2982875.34     13941441.47
      2982235.48     13941403.27
#Sta/Elev= 30
  4559.7   205.4  4694.7   207.1  4889.7   207.6  4949.7   207.1  4964.7   206.4
  4979.7   204.3  4994.7   200.6 4994.75  197.97    4997  193.51  4997.7  193.33
  5002.6  193.46  5006.5  196.89 5007.21  197.99  5009.7   202.1  5024.7   203.9
  5039.7   207.6  5054.7     210  5069.7   210.6    5101   210.7    5116   209.8
    5131   207.6    5146   207.2    5206   207.5    5236   206.9  5285.4  207.05
    5326   206.2    5386   206.4    5536   204.2    5611   205.2    5727   205.3
#Mann= 4 ,-1 , 0
  4559.7    .045       0 4994.75     .05       0 5007.21     .07       0
  5285.4     .04       0
Bank Sta=4994.75,5007.21
XS Rating Curve= 0
Exp/Cntr=.3,.1