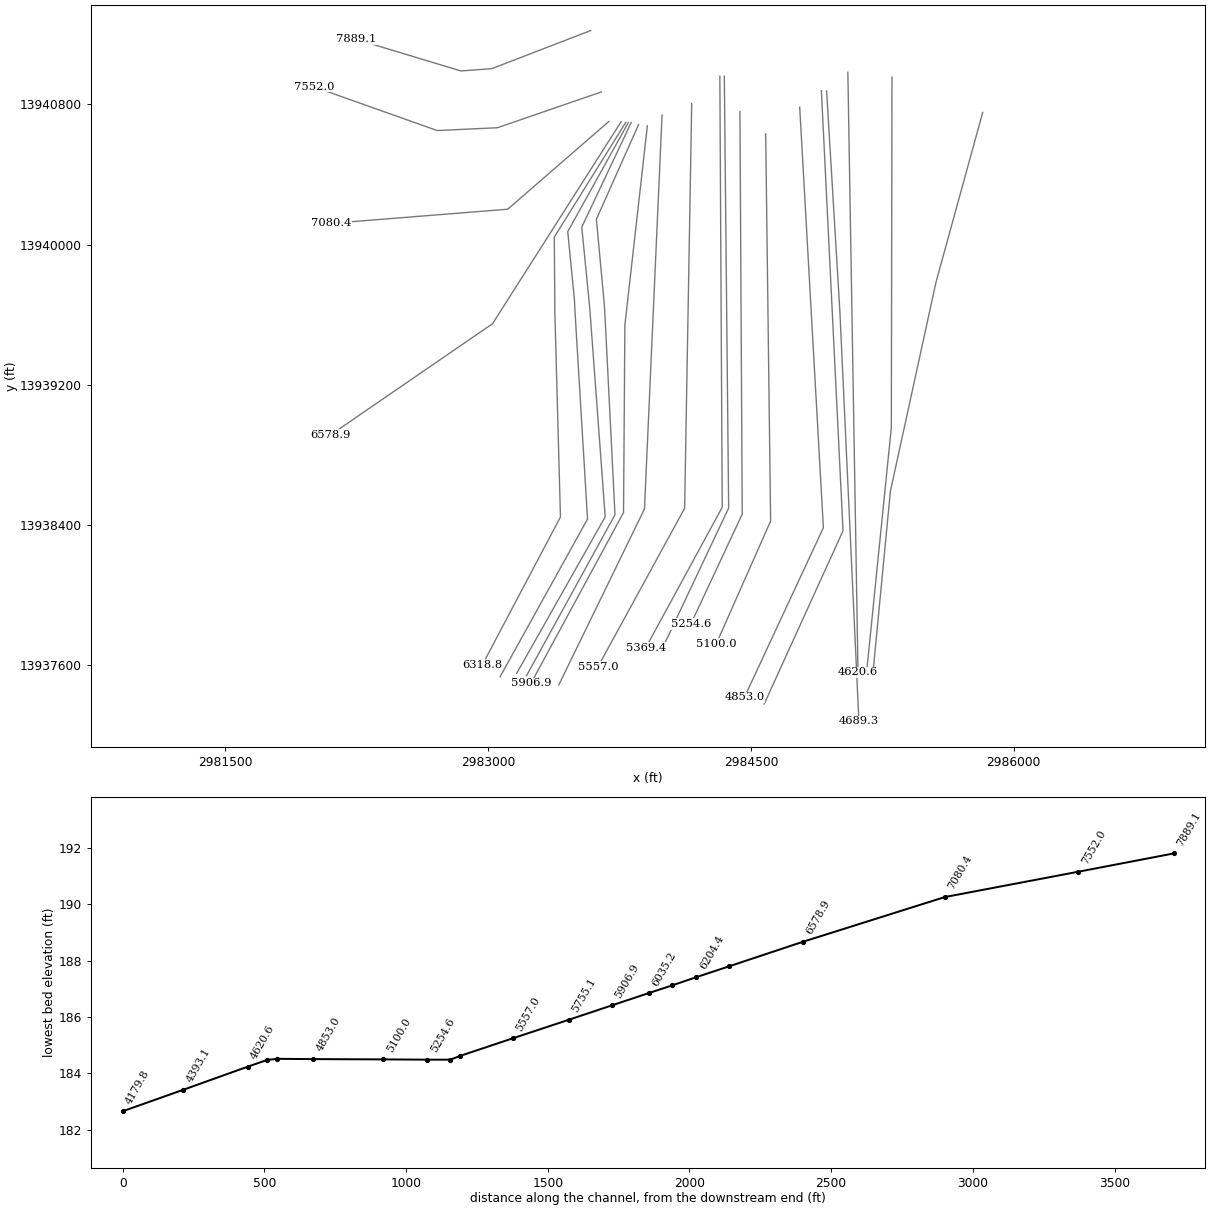
HEC-RAS study L114-01-00.PRJ: L114-01-00

--- L114-01-00.g01 (geometry) --- (continued)

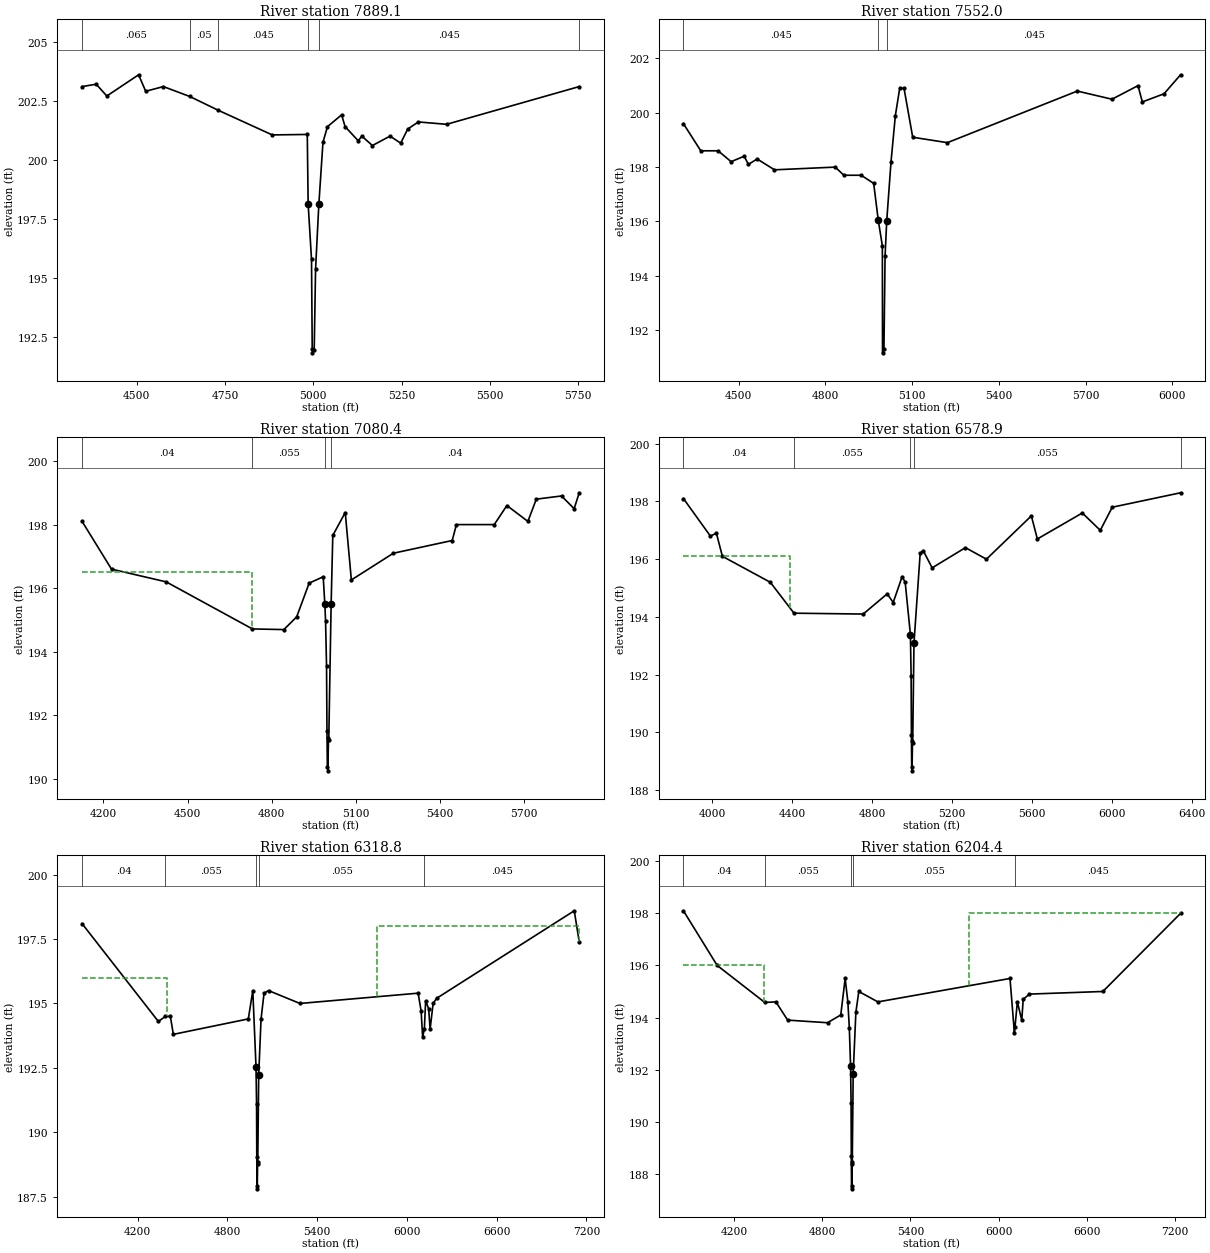
Type RM Length L Ch R = 1 ,7889.1  ,343.9,337.1,336.2
BEGIN DESCRIPTION:
Cross Section XS16
END DESCRIPTION:
XS GIS Cut Line= 4
    2983584.7437   13941221.6951     2983020.904   13941004.2888
    2982844.2436   13940991.1052    2982245.6543   13941171.8149
#Sta/Elev= 30
  4345.8   203.1  4385.8   203.2  4415.8   202.7  4505.8   203.6  4525.8   202.9
  4575.8   203.1  4650.4  202.68  4730.4   202.1  4883.9  201.05    4983  201.07
  4985.5  198.11    4995  195.77    4997  191.99  4997.7  191.81  5002.6  191.94
  5006.5  195.37  5015.7   198.1  5027.4  200.74  5040.1   201.4  5080.1   201.9
  5090.1   201.4  5127.3   200.8  5137.3     201  5167.3   200.6  5217.3     201
  5247.3   200.7  5267.3   201.3  5297.3   201.6  5377.3   201.5  5752.5   203.1
#Mann= 6 ,-1 , 0
  4345.8    .065       0  4650.4     .05       0  4730.4    .045       0
  4985.5     .05       0  5015.7    .045       0  5752.5      .2       0
Bank Sta=4985.5,5015.7
XS Rating Curve= 0
Exp/Cntr=.3,.1

Type RM Length L Ch R = 1 ,7552.0  ,410.1,471.6,472.5
BEGIN DESCRIPTION:
Cross Section XS15.4
END DESCRIPTION:
XS GIS Cut Line= 4
      2983646.69     13940871.46      2983052.84     13940667.02
      2982708.86      13940650.8      2982004.69     13940900.67
#Sta/Elev= 30
    4309   199.6    4369   198.6    4429   198.6    4474   198.2    4519   198.4
    4534   198.1    4564   198.3    4624   197.9    4834     198    4864   197.7
    4924   197.7  4967.1   197.4    4983  196.04  4997.1   195.1  4997.7  191.16
  5002.6  191.29  5006.5  194.72  5012.1     196  5027.1   198.2  5042.1   199.9
  5057.1   200.9  5072.1   200.9  5102.1   199.1  5222.1   198.9  5671.4   200.8
  5791.4   200.5  5881.4     201  5896.4   200.4  5971.4   200.7  6028.6   201.4
#Mann= 3 ,-1 , 0
    4309    .045       0    4983     .05       0  5012.1    .045       0
Bank Sta=4983,5012.1
XS Rating Curve= 0
Exp/Cntr=.3,.1

Type RM Length L Ch R = 1 ,7080.4  ,300,501.5,549.2
BEGIN DESCRIPTION:
Left Ineffective for transitioning with upstream cross section
Cross Section XS15
END DESCRIPTION:
XS GIS Cut Line= 3
    2983689.5093   13940703.2443    2983111.1835   13940201.6155
    2982106.2298   13940121.4658
#Sta/Elev= 30
  4123.6   198.1  4228.6   196.6  4423.6   196.2  4731.4  194.72  4843.6   194.7
  4889.2   195.1  4933.8  196.16  4983.9  196.36 4989.67   195.5  4992.3  194.98
  4995.8  193.54  4997.3  191.51  4998.7  190.38  5000.5  190.26  5002.7   191.3
  5003.7  191.22  5012.2  195.51  5018.1  197.66  5062.5  198.38  5084.3  196.26
  5234.2   197.1  5444.2   197.5  5459.2     198  5594.2     198  5639.2   198.6
  5714.2   198.1  5744.2   198.8  5834.2   198.9  5879.2   198.5  5897.3     199
#Mann= 4 ,-1 , 0
  4123.6     .04       0  4731.4    .055       0 4989.67     .05       0
  5012.2     .04       0
#XS Ineff= 2 , 0
       0    4730   196.5               0
Permanent Ineff=
       F       F
Bank Sta=4989.67,5012.2
XS Rating Curve= 0
Exp/Cntr=.3,.1

Type RM Length L Ch R = 1 ,6578.9  ,61.9,260.1,386.8
BEGIN DESCRIPTION:
Left Ineffective for transitioning with upstream cross section
Cross Section XS14.5
END DESCRIPTION:
XS GIS Cut Line= 3
    2983758.5464   13940701.0097    2983024.8685   13939548.0873
    2982100.0644   13938913.0552
#Sta/Elev= 30
  3856.1   198.1  3991.1   196.8  4021.1   196.9  4051.1   196.1  4291.1   195.2
  4409.5  194.13  4756.1   194.1  4876.1   194.8  4906.1   194.5  4951.1   195.4
  4966.1   195.2  4992.3  193.39  4995.8  191.95  4997.3  189.92  4998.7  188.79
  5000.5  188.67  5002.7  189.71  5003.7  189.63  5010.1  193.09  5041.1   196.2
  5056.1   196.3  5101.1   195.7  5267.7   196.4  5372.7     196  5597.7   197.5
  5627.7   196.7  5852.7   197.6  5942.7     197  6002.7   197.8  6344.5   198.3
#Mann= 5 ,-1 , 0
  3856.1     .04       0  4409.5    .055       0  4992.3     .05       0
  5010.1    .055       0  6344.5      .2       0
#XS Ineff= 2 , 0
       0    4390   196.1               0
Permanent Ineff=
       F       F
Bank Sta=4992.3,5010.1
XS Rating Curve= 0
Exp/Cntr=.3,.1

Type RM Length L Ch R = 1 ,6318.8  ,89.6,114.4,136.4
XS GIS Cut Line= 6
    2983785.2241   13940697.1157    2983377.4094   13940042.7043
    2983380.2061   13939671.5868    2983380.2061   13939627.5457
    2983412.4814   13938444.5135    2982967.3176   13937601.6543
#Sta/Elev= 30
  3829.6   198.1  4339.6   194.3  4386.3   194.5  4419.6   194.5  4439.6   193.8
  4940.7   194.4  4970.7   195.5  4992.3  192.52  4995.8  191.08  4997.3  189.05
  4998.7  187.92  5000.5   187.8  5002.7  188.84  5003.7  188.76  5010.1  192.22
  5025.9   194.4  5045.9   195.4  5075.9   195.5  5285.9     195  6075.9   195.4
  6095.9   194.7  6105.9   193.7  6117.5  194.01  6125.9   195.1  6145.9   194.8
  6155.9     194  6175.9     195  6199.3   195.2  7119.3   198.6  7152.5   197.4
#Mann= 5 ,-1 , 0
  3829.6     .04       0  4386.3    .055       0  4992.3    .045       0
  5010.1    .055       0  6117.5    .045       0
#XS Ineff= 2 , 0
       0    4400     196    5800       0     198
Permanent Ineff=
       F       F
Bank Sta=4992.3,5010.1
XS Rating Curve= 0
Exp/Cntr=.5,.3

Type RM Length L Ch R = 1 ,6204.4  ,83.5,84.6,85.7
BEGIN DESCRIPTION:
Upstream Section of Bridge/Culvert/Weir
END DESCRIPTION:
XS GIS Cut Line= 6
    2983799.7553    13940696.221    2983454.2131   13940073.8732
     2983492.866    13939677.448    2983495.8661   13939612.9476
    2983567.1026   13938432.6494     2983067.983   13937532.4468
#Sta/Elev= 30
  3853.7   198.1  4083.7     196  4407.8  194.58  4483.7   194.6  4563.7   193.9
  4835.5   193.8  4925.5   194.1  4955.5   195.5  4973.8   194.6  4983.8   193.6
  4992.3  192.14  4995.8   190.7  4997.3  188.67  4998.7  187.54  5000.5  187.42
  5002.7  188.46  5003.7  188.38  5010.1  191.84  5028.4   194.2  5048.4     195
  5178.4   194.6  6078.4   195.5  6108.4   193.4  6112.1  193.62  6128.4   194.6
  6158.4   193.9  6168.4   194.7  6210.9   194.9  6710.9     195  7240.2     198
#Mann= 5 ,-1 , 0
  3853.7     .04       0  4407.8    .055       0  4992.3    .045       0
  5010.1    .055       0  6112.1    .045       0
#XS Ineff= 4 ,-1
  3853.7    4400     196    4400    4986     190    5014    5800     190
    5800  7240.2     198
Permanent Ineff=
       F       F       F       F
Bank Sta=4992.3,5010.1
XS Rating Curve= 0
Exp/Cntr=.5,.3

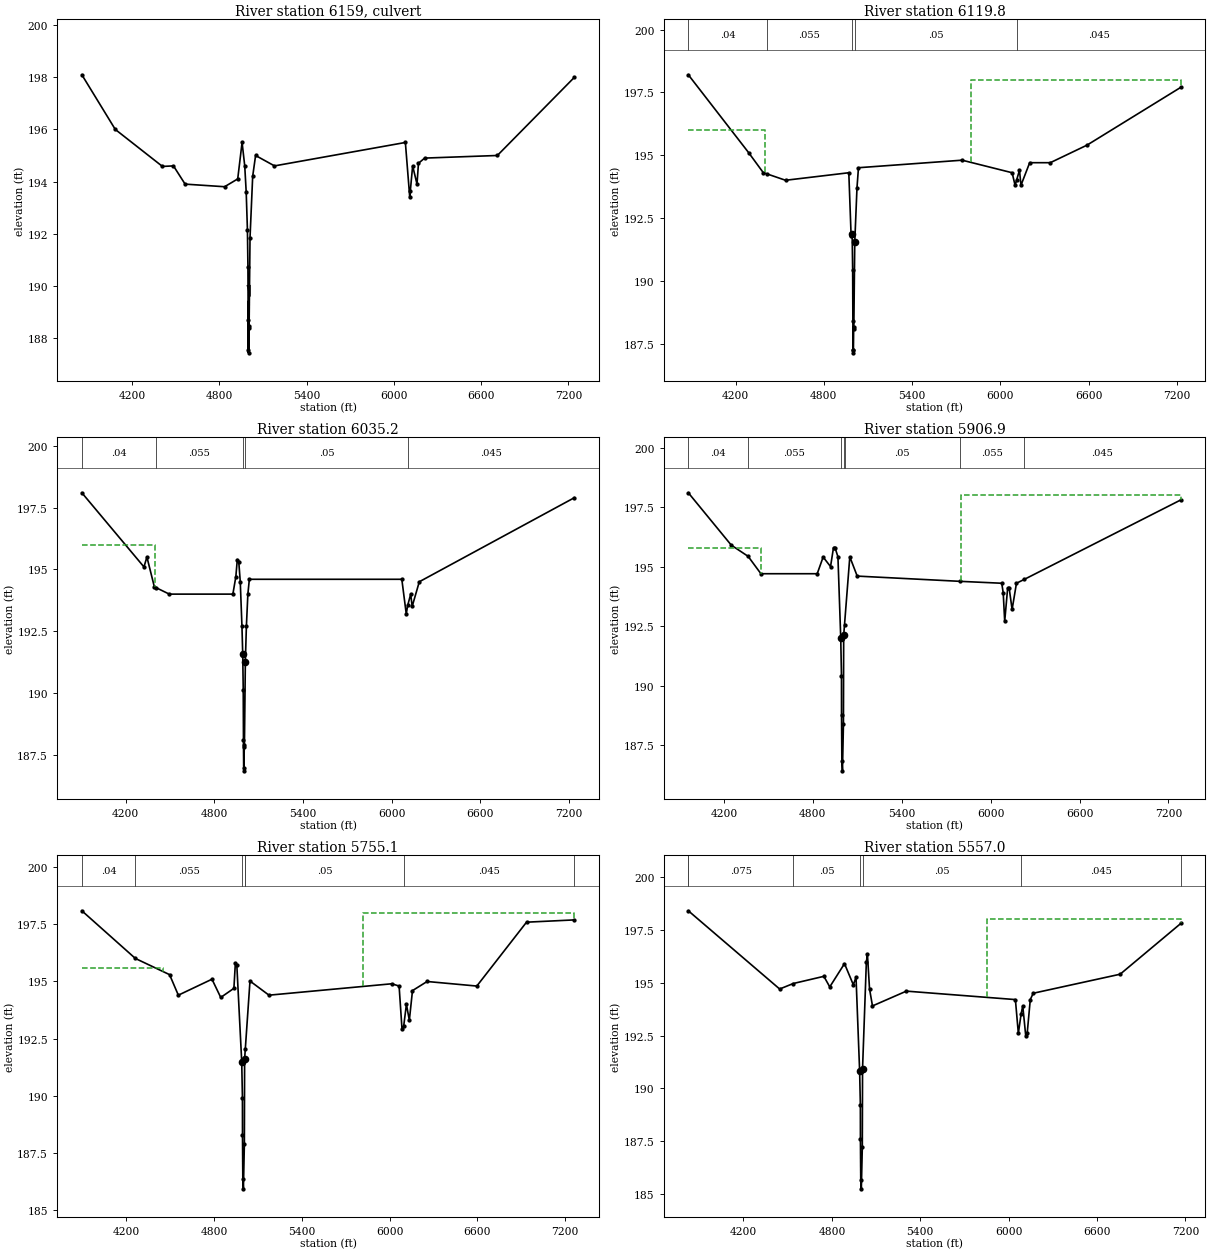
Type RM Length L Ch R = 2 ,6159    ,,,
BEGIN DESCRIPTION:
Private Road 1420 FEET US MCGEE ROAD
END DESCRIPTION:
Bridge Culvert--1,0,-1,-1, 0
Deck Dist Width WeirC Skew NumUp NumDn MinLoCord MaxHiCord MaxSubmerge Is_Ogee
37.5,15,2.6,0, 3, 3, , , .95, 0, 0,0,,
  4992.3  5010.1  5010.1
     190   189.6     190
                        
  4992.3  5010.1  5010.1
     190   189.6     190
                        
BR Coef=-1 , 0 , 0 ,, 0 ,,,.8,0,,0,
WSPro=,,,, 1 ,,,, 0 ,,,, 0 ,,,,-1 ,-1 ,-1 , 0 , 0 , 0 , 0 , 0
Multiple Barrel Culv=1,2,,20,.027,.9,1,2,3,187.42,187.13, 3,Culvert #1  , 0 ,35
    4997    4997    5000    5000    5003    5003
Culvert Bottom n=.027
BC Design=,, 0 ,, 0 ,,,,,,

Type RM Length L Ch R = 1 ,6119.8  ,83.5,84.6,85.4
BEGIN DESCRIPTION:
Downstream Section of Bridge/Culvert/Weir
END DESCRIPTION:
XS GIS Cut Line= 6
     2983816.682   13940697.1157    2983534.2023   13940099.4783
    2983577.0651   13939666.0705    2983582.4446   13939601.5177
    2983667.9798   13938445.3624    2983162.3568   13937551.3216
#Sta/Elev= 28
  3878.6   198.2  4288.6   195.1  4388.6   194.3  4410.2  194.26  4539.6     194
  4969.6   194.3  4985.2   191.8  4992.3  191.85  4995.8  190.41  4997.3  188.38
  4998.7  187.25  5000.5  187.13  5000.9  187.26  5002.7  188.17  5003.7  188.09
  5010.1  191.55  5025.2   193.7  5035.2   194.5  5739.9   194.8  6079.9   194.3
  6099.9   193.8    6110     194  6129.9   194.4  6139.9   193.8  6199.2   194.7
  6339.2   194.7  6589.2   195.4  7226.4   197.7
#Mann= 5 ,-1 , 0
  3878.6     .04       0  4410.2    .055       0  4992.3    .045       0
  5010.1     .05       0    6110    .045       0
#XS Ineff= 4 ,-1
  3878.6    4400     196    4400    4986     190    5014    5800     190
    5800  7226.4     198
Permanent Ineff=
       F       F       F       F
Bank Sta=4992.3,5010.1
XS Rating Curve= 0
Exp/Cntr=.5,.3

Type RM Length L Ch R = 1 ,6035.2  ,186.2,128.3,112.9
XS GIS Cut Line= 6
    2983858.3548   13940684.3732    2983617.6788   13940144.3471
    2983662.2643    13939665.025    2983666.2299   13939604.2191
    2983723.8539   13938457.3879    2983218.9811   13937538.7384
#Sta/Elev= 30
  3904.5   198.1  4324.5   195.1  4344.5   195.5  4394.5   194.3  4406.6  194.26
  4495.7     194  4925.7     194  4945.7   194.7  4955.7   195.4  4965.7   195.3
  4975.7   194.5  4987.1   192.7  4992.3  191.57  4995.8  190.13  4997.3   188.1
  4998.7  186.97  5000.5  186.85  5002.7  187.89  5003.7  187.81  5010.1  191.27
  5017.1   192.7  5027.1     194  5037.1   194.6  6068.1   194.6  6098.1   193.2
  6107.8  193.54  6128.1     194  6138.1   193.5  6186.3   194.5  7234.6   197.9
#Mann= 5 ,-1 , 0
  3904.5     .04       0  4406.6    .055       0  4992.3    .045       0
  5010.1     .05       0  6107.8    .045       0
#XS Ineff= 2 , 0
       0    4400     196    5800       0
Permanent Ineff=
       F       F
Bank Sta=4992.3,5010.1
XS Rating Curve= 0
Exp/Cntr=.3,.1

Type RM Length L Ch R = 1 ,5906.9  ,135.5,151.8,161.8
BEGIN DESCRIPTION:
Left and right Ineffectives used to transition with upstream and downstream cross sections
Cross Section XS13.67
END DESCRIPTION:
XS GIS Cut Line= 4
    2983908.7053   13940677.5551    2983780.3197    13939539.307
    2983772.6409   13938469.8935    2983244.1475   13937494.6973
#Sta/Elev= 30
  3959.4   198.1  4249.4   195.9  4363.1  195.43  4449.4   194.7  4829.4   194.7
  4869.4   195.4  4919.4     195  4939.4   195.8  4949.4   195.8  4969.3  195.41
  4988.2     192  4993.2   190.4  4993.6  188.78  4995.8  186.85  4999.8  186.42
  5006.4  188.38  5008.1  192.11  5013.6  192.55  5049.4  195.41  5099.4   194.6
  5793.8  194.38  6074.9   194.3  6084.9   193.9  6094.9   192.7  6114.9   194.1
  6124.9   194.1  6144.9   193.2  6174.3   194.3  6226.5  194.46  7283.5   197.8
#Mann= 7 ,-1 , 0
  3959.4     .04       0  4363.1    .055       0  4988.2    .045       0
  5008.1    .055       0  5013.6     .05       0  5793.8    .055       0
  6226.5    .045       0
#XS Ineff= 2 , 0
       0    4450   195.8    5800       0     198
Permanent Ineff=
       F       F
Bank Sta=4988.2,5008.1
XS Rating Curve= 0
Exp/Cntr=.3,.1

Type RM Length L Ch R = 1 ,5755.1  ,191.8,198.1,215.2
BEGIN DESCRIPTION:
Left and right Ineffectives used to transition with upstream and downstream cross sections
Cross Section XS13.33
END DESCRIPTION:
XS GIS Cut Line= 3
    2983992.6034   13940739.5992    2983892.2669   13938490.3735
    2983403.2322   13937486.0497
#Sta/Elev= 30
  3894.8   198.1  4260.9  196.01  4494.8   195.3  4554.8   194.4  4784.8   195.1
  4844.8   194.3  4934.8   194.7  4944.8   195.8  4954.8  195.72  4988.2  191.49
  4993.2  189.89  4993.6  188.27  4995.8  186.34  4999.8  185.91  5006.4  187.87
  5008.1   191.6  5012.8  192.04  5044.8  195.02  5174.8   194.4  6014.8   194.9
  6064.8   194.8  6084.8   192.9  6096.3  193.05  6114.8     194  6134.8   193.3
  6156.3   194.6  6256.3     195  6596.3   194.8  6936.3   197.6  7263.3   197.7
#Mann= 7 ,-1 , 0
  3894.8     .04       0  4260.9    .055       0  4988.2    .045       0
  5008.1    .055       0  5012.8     .05       0  6096.3    .045       0
  7263.3      .2       0
#XS Ineff= 2 , 0
       0    4450   195.6    5820       0     198
Permanent Ineff=
       F       F
Bank Sta=4988.2,5008.1
XS Rating Curve= 0
Exp/Cntr=.3,.1

Type RM Length L Ch R = 1 ,5557.0  ,184.7,187.6,202.2
BEGIN DESCRIPTION:
Cross Section XS13
END DESCRIPTION:
XS GIS Cut Line= 4
    2984161.9533   13940804.7323    2984121.4301   13938494.0697
    2983687.0209   13937699.5955    2983626.5468   13937588.9968
#Sta/Elev= 30
  3825.5   198.4  4445.5   194.7  4537.8  194.96  4745.5   195.3  4785.5   194.8
  4885.5   195.9  4945.5   194.9  4963.8  195.26  4988.2  190.83  4993.2  189.23
  4993.6  187.61  4995.8  185.68  4999.8  185.25  5006.4  187.21  5008.1  190.94
  5033.8  195.96  5041.1  196.36  5055.5   194.7  5075.5   193.9  5305.5   194.6
  6045.5   194.2  6065.5   192.6  6084.5  193.53  6095.5   193.9  6115.5   192.5
  6125.5   192.6  6146.5   194.2  6166.5   194.5  6756.5   195.4  7168.1   197.8
#Mann= 7 , 1 , 0
  3825.5      .2       0  3825.5    .075       0  4537.8     .05       0
  4988.2    .045       0  5008.1     .05       0  6084.5    .045       0
  7168.1      .2       0
#XS Ineff= 2 , 0
       0                    5850       0     198
Permanent Ineff=
       F       F
Bank Sta=4988.2,5008.1
XS Rating Curve= 0
Exp/Cntr=.5,.3

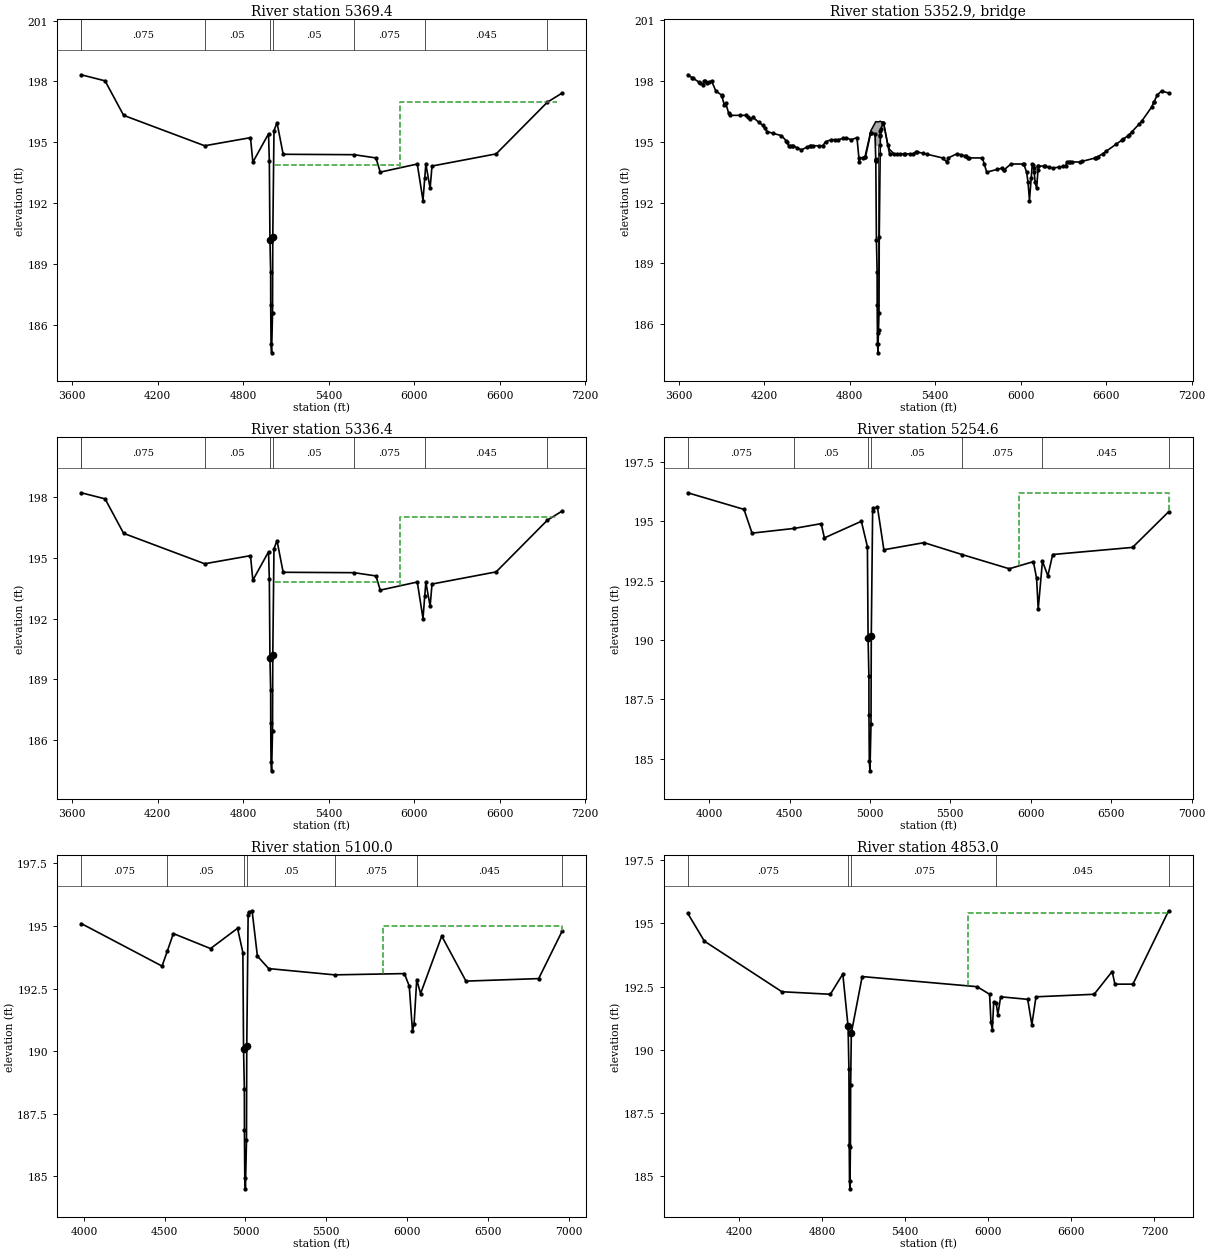
Type RM Length L Ch R = 1 ,5369.4  ,33,33,33
BEGIN DESCRIPTION:
Upstream Section of Bridge/Culvert/Weir
END DESCRIPTION:
XS GIS Cut Line= 4
    2984322.5516   13940960.7847    2984336.1166    13938500.165
    2984024.0258   13937926.5254    2983899.9944    13937698.549
#Sta/Elev= 30
  3664.8  198.33  3831.8  198.03  3961.8  196.33  4530.4  194.83  4851.8  195.23
  4868.3  194.02  4978.3  195.42    4984  194.06  4988.2   190.2  4993.2   188.6
  4993.6  186.98  4995.8  185.05  4999.8  184.62  5006.4  186.58  5008.1  190.31
  5016.5  195.57  5037.8  195.97  5080.9  194.41  5578.3  194.39  5731.8  194.23
  5761.8  193.53  6021.8  193.93  6061.8  192.13  6074.1  193.24  6081.8  193.93
  6111.8  192.73    6125  193.83    6575  194.43  6934.4  196.98    7038  197.43
#Mann= 8 , 1 , 0
  3664.8      .2       0  3664.8    .075       0  4530.4     .05       0
  4988.2    .045       0  5008.1     .05       0  5578.3    .075       0
  6074.1    .045       0  6934.4      .2       0
#XS Ineff= 3 ,-1
    4800    4975   194.3    5025    5900   193.9  5900.5    7000     197
Permanent Ineff=
       F       F       F
Bank Sta=4988.2,5008.1
XS Rating Curve= 0
Exp/Cntr=.5,.3

Type RM Length L Ch R = 3 ,5352.9  ,,,
BEGIN DESCRIPTION:
Access Rd 615 FEET US MCGEE ROAD
- needs rail height in field + deck height
Structure ID: L114-01-00-S3A
END DESCRIPTION:
Bridge Culvert--1,0,-1,-1, 0
Deck Dist Width WeirC Skew NumUp NumDn MinLoCord MaxHiCord MaxSubmerge Is_Ogee
10,13,2.6,0, 31, 31, , , .95, 0, 1,1,,
  4908.8  4911.4  4948.2  4949.8  4978.3  4983.5 4983.62 4983.71 4983.89    4984
  4988.2  4993.2  4993.6  4995.8  4999.8  4999.9  5002.4  5003.2  5006.4  5008.1
 5014.66  5015.4 5016.08 5016.19  5016.5  5019.3  5037.8  5037.9  5067.7  5080.9
  5114.8
  194.24  194.37   195.5  195.55  195.92  195.99  195.99  195.99  195.99  195.99
  195.99  195.98  195.98  195.98  195.98  195.98  195.98  195.98  195.99  195.99
  196.01  196.01  196.01  196.01  196.01  195.99  195.95  195.95  194.86  194.62
  194.39
  194.24  194.24  195.43  195.43  195.39  194.15  194.12  194.79  194.79  194.79
  194.79  194.78  194.78  194.78  194.78  194.78  194.78  194.78  194.79  194.79
  194.81  194.85  195.28  195.35  195.54  195.64  195.94  195.94  194.86  194.38
  194.39
  4908.8  4911.4  4948.2  4949.8  4978.3  4983.5 4983.62 4983.71 4983.89    4984
  4988.2  4993.2  4993.6  4995.8  4999.8  4999.9  5002.4  5003.2  5006.4  5008.1
 5014.66  5015.4 5016.08 5016.19  5016.5  5019.3  5037.8  5037.9  5067.7  5080.9
  5114.8
  194.14  194.37   195.5  195.55  195.92  195.99  195.99  195.99  195.99  195.99
  195.99  195.98  195.98  195.98  195.98  195.98  195.98  195.98  195.99  195.99
  196.01  196.01  196.01  196.01  196.01  195.99  195.95  195.95  194.86  194.62
  194.29
  194.14  194.24  195.43  195.43  195.39  194.15  194.12  194.79  194.79  194.79
  194.79  194.78  194.78  194.78  194.78  194.78  194.78  194.78  194.79  194.79
  194.81  194.85  195.28  195.35  195.54  195.64  195.94  195.94  194.86  194.38
  194.29
Pier Skew, UpSta & Num, DnSta & Num=  ,4999.9, 2 ,4999.9, 2 , 0 , 0 , 0 ,,
       1       1
  183.63  195.78
       1       1
  183.53  195.68
Abutment Skew #Up #Dn= , 2 , 2
 5014.76 5016.28
  194.45  195.28
 5014.76 5016.28
  194.35  195.18
BR Coef= 1 , 1 , 1 ,1.25, 0 ,,,.8,-1,2,0,
WSPro=,,,, 1 ,,,, 0 ,,,, 0 ,,,,-1 ,-1 ,-1 , 0 , 0 , 0 , 0 , 0
BR U #Sta/Elev= 159
  3664.8   198.3  3694.8  198.16  3704.8  198.12  3744.8  197.93  3751.8   197.9
  3771.8   197.8  3781.8     198  3784.8  197.99  3801.8   197.9  3814.8  197.94
  3831.8     198  3861.8   197.5  3901.8   197.3  3904.8  197.23  3921.8   196.8
  3931.8   196.9  3951.8   196.4  3961.8   196.3  4034.8   196.3  4071.8   196.3
  4084.8  196.21  4101.8   196.1  4121.8   196.2  4164.8  195.95  4191.8   195.8
  4204.8  195.67  4221.8   195.5  4264.8  195.41  4321.8   195.3  4354.8  195.05
  4361.8     195  4371.8   194.8  4384.8   194.8  4394.8   194.8  4401.8   194.8
  4431.8   194.7  4461.8   194.6  4504.8  194.74  4521.8   194.8  4530.4   194.8
  4544.8   194.8  4584.8   194.8  4611.8   194.8  4631.8     195  4671.8   195.1
  4694.8   195.1  4721.8   195.1  4754.8  195.17  4771.8   195.2  4811.8   195.1
  4851.8   195.2  4868.3  193.99  4868.9   194.2  4894.8  194.22  4908.8  194.24
  4911.4  194.24  4948.2  195.43  4949.8  195.43  4978.3  195.39  4983.5  194.15
 4983.62  194.12 4983.71   194.1 4983.89  194.06    4984  194.03  4988.2  190.17
  4993.2  188.57  4993.6  186.95  4995.8  185.02  4999.8  184.59  4999.9  185.02
  5002.4  185.56  5003.2  185.73  5006.4  186.55  5008.1  190.28 5014.66  194.39
  5015.4  194.85 5016.08  195.28 5016.19  195.35  5016.5  195.54  5019.3  195.64
  5037.8  195.94  5037.9  195.94  5067.7  194.86  5080.9  194.38  5114.8  194.39
  5134.8  194.39  5154.8  194.39  5184.8   194.4  5191.8   194.4  5224.8   194.4
  5241.8   194.4  5264.8  194.48  5271.8   194.5  5314.8  194.43  5344.8  194.38
  5451.8   194.2  5481.8     194  5491.8   194.2  5551.8   194.4  5578.3  194.36
  5611.8   194.3  5614.8  194.29  5631.8   194.2  5634.8   194.2  5731.8   194.2
  5744.8   193.9  5761.8   193.5  5834.8  193.63  5871.8   193.7  5881.8   193.6
  5884.8  193.62  5931.8   193.9  6014.8   193.9  6021.8   193.9  6041.8   193.5
  6051.8     193  6061.8   192.1  6074.1  193.21  6081.8   193.9  6084.8  193.84
  6091.8   193.7  6094.8  193.49  6101.8     193  6111.8   192.7  6121.8   193.6
  6124.8  193.79    6125   193.8    6165   193.8  6170.2  193.79  6200.2  193.74
    6225   193.7  6270.2  193.75  6300.2  193.78    6315   193.8    6325     194
  6340.2     194    6345     194  6360.2     194    6415     194  6430.2  194.03
    6525   194.2  6530.2  194.22  6540.2  194.26    6575   194.4  6600.2  194.53
  6668.1  194.87  6708.1  195.07  6718.1  195.12    6755   195.3  6758.1  195.32
  6778.1  195.47  6828.1  195.85    6848     196    6918   196.7  6934.3  196.94
  6934.4  196.95    6958   197.3    6988   197.5    7038   197.4
BR U #Mann= 8
  3664.8      .2  3664.8     .06  4530.4    .045  4988.2     .04  5008.1    .045
  5578.3     .06  6074.1     .04  6934.4      .2
BR U Banks=4988.2,5008.1
BR D #Sta/Elev= 159
  3664.8   198.2  3694.8  198.06  3704.8  198.02  3744.8  197.83  3751.8   197.8
  3771.8   197.7  3781.8   197.9  3784.8  197.89  3801.8   197.8  3814.8  197.84
  3831.8   197.9  3861.8   197.4  3901.8   197.2  3904.8  197.13  3921.8   196.7
  3931.8   196.8  3951.8   196.3  3961.8   196.2  4034.8   196.2  4071.8   196.2
  4084.8  196.11  4101.8     196  4121.8   196.1  4164.8  195.85  4191.8   195.7
  4204.8  195.57  4221.8   195.4  4264.8  195.31  4321.8   195.2  4354.8  194.95
  4361.8   194.9  4371.8   194.7  4384.8   194.7  4394.8   194.7  4401.8   194.7
  4431.8   194.6  4461.8   194.5  4504.8  194.64  4521.8   194.7  4530.4   194.7
  4544.8   194.7  4584.8   194.7  4611.8   194.7  4631.8   194.9  4671.8     195
  4694.8     195  4721.8     195  4754.8  195.07  4771.8   195.1  4811.8     195
  4851.8   195.1  4868.3  193.89  4868.9   194.1  4894.8  194.12  4908.8  194.14
  4911.4  194.14  4948.2  195.33  4949.8  195.33  4978.3  195.29  4983.5  194.05
 4983.62  194.02 4983.71     194 4983.89  193.96    4984  193.93  4988.2  190.07
  4993.2  188.47  4993.6  186.85  4995.8  184.92  4999.8  184.49  4999.9  184.92
  5002.4  185.46  5003.2  185.63  5006.4  186.45  5008.1  190.18 5014.66  194.29
  5015.4  194.75 5016.08  195.18 5016.19  195.25  5016.5  195.44  5019.3  195.54
  5037.8  195.84  5037.9  195.84  5067.7  194.76  5080.9  194.28  5114.8  194.29
  5134.8  194.29  5154.8  194.29  5184.8   194.3  5191.8   194.3  5224.8   194.3
  5241.8   194.3  5264.8  194.38  5271.8   194.4  5314.8  194.33  5344.8  194.28
  5451.8   194.1  5481.8   193.9  5491.8   194.1  5551.8   194.3  5578.3  194.26
  5611.8   194.2  5614.8  194.19  5631.8   194.1  5634.8   194.1  5731.8   194.1
  5744.8   193.8  5761.8   193.4  5834.8  193.53  5871.8   193.6  5881.8   193.5
  5884.8  193.52  5931.8   193.8  6014.8   193.8  6021.8   193.8  6041.8   193.4
  6051.8   192.9  6061.8     192  6074.1  193.11  6081.8   193.8  6084.8  193.74
  6091.8   193.6  6094.8  193.39  6101.8   192.9  6111.8   192.6  6121.8   193.5
  6124.8  193.69    6125   193.7    6165   193.7  6170.2  193.69  6200.2  193.64
    6225   193.6  6270.2  193.65  6300.2  193.68    6315   193.7    6325   193.9
  6340.2   193.9    6345   193.9  6360.2   193.9    6415   193.9  6430.2  193.93
    6525   194.1  6530.2  194.12  6540.2  194.16    6575   194.3  6600.2  194.43
  6668.1  194.77  6708.1  194.97  6718.1  195.02    6755   195.2  6758.1  195.22
  6778.1  195.37  6828.1  195.75    6848   195.9    6918   196.6  6934.3  196.84
  6934.4  196.85    6958   197.2    6988   197.4    7038   197.3
BR D #Mann= 8
  3664.8      .2  3664.8     .06  4530.4    .045  4988.2     .04  5008.1    .045
  5578.3     .06  6074.1     .04  6934.4      .2
BR D Banks=4988.2,5008.1
BC Design=,, 0 ,, 0 ,,,,,,
BC HTab HWMax=198.33

Type RM Length L Ch R = 1 ,5336.4  ,83.8,81.8,80.1
BEGIN DESCRIPTION:
Downstream Section of Bridge/Culvert/Weir
END DESCRIPTION:
XS GIS Cut Line= 4
    2984348.1356   13940960.9679    2984372.7896   13938495.5699
    2984160.1519   13938045.3749    2983985.1291   13937674.8179
#Sta/Elev= 30
  3664.8   198.2  3831.8   197.9  3961.8   196.2  4530.4   194.7  4851.8   195.1
  4868.3  193.89  4978.3  195.29    4984  193.93  4988.2  190.07  4993.2  188.47
  4993.6  186.85  4995.8  184.92  4999.8  184.49  5006.4  186.45  5008.1  190.18
  5016.5  195.44  5037.8  195.84  5080.9  194.28  5578.3  194.26  5731.8   194.1
  5761.8   193.4  6021.8   193.8  6061.8     192  6074.1  193.11  6081.8   193.8
  6111.8   192.6    6125   193.7    6575   194.3  6934.4  196.85    7038   197.3
#Mann= 8 , 1 , 0
  3664.8      .2       0  3664.8    .075       0  4530.4     .05       0
  4988.2    .045       0  5008.1     .05       0  5578.3    .075       0
  6074.1    .045       0  6934.4      .2       0
#XS Ineff= 3 ,-1
    4800    4975   194.1    5025    5900   193.8  5900.5    7000     197
Permanent Ineff=
       F       F       F
Bank Sta=4988.2,5008.1
XS Rating Curve= 0
Exp/Cntr=.5,.3

Type RM Length L Ch R = 1 ,5254.6  ,153.4,154.6,157.4
BEGIN DESCRIPTION:
Cross Section XS12
END DESCRIPTION:
XS GIS Cut Line= 4
    2984437.2449   13940759.5352    2984450.3902   13938460.8041
    2984315.5697    13938172.567    2984156.9867   13937833.5275
#Sta/Elev= 30
  3866.4   196.2  4216.4   195.5  4266.4   194.5  4529.2   194.7  4696.4   194.9
  4716.4   194.3  4946.4     195    4984  193.93  4988.2  190.07  4993.2  188.47
  4993.6  186.85  4995.8  184.92  4999.8  184.49  5006.4  186.45  5008.1  190.18
  5016.5  195.44  5019.3  195.54  5046.4   195.6  5086.4   193.8  5336.4   194.1
  5572.1   193.6  5866.4     193  6016.4   193.3  6036.4   192.6  6046.4   191.3
  6072.8  193.32  6106.4   192.7  6136.4   193.6  6633.4   193.9  6857.7   195.4
#Mann= 7 ,-1 , 0
  3866.4    .075       0  4529.2     .05       0  4988.2    .045       0
  5008.1     .05       0  5572.1    .075       0  6072.8    .045       0
  6857.7      .2       0
#XS Ineff= 2 , 0
       0                    5925       0   196.2
Permanent Ineff=
       F       F
Bank Sta=4988.2,5008.1
XS Rating Curve= 0
Exp/Cntr=.3,.1

Type RM Length L Ch R = 1 ,5100.0  ,238.5,247,271.7
BEGIN DESCRIPTION:
Cross Section XS 11.5
END DESCRIPTION:
XS GIS Cut Line= 3
    2984584.3317    13940631.989    2984612.4592   13938421.1678
    2984302.5055   13937721.3224
#Sta/Elev= 30
  3983.8   195.1  4483.8   193.4  4516.9  194.01  4553.8   194.7  4783.8   194.1
  4951.1  194.91    4984  193.94  4988.2  190.08  4993.2  188.48  4993.6  186.86
  4995.8  184.93  4999.8   184.5  5006.4  186.46  5008.1  190.19  5016.5  195.45
  5019.3  195.55  5041.1  195.61  5073.8   193.8  5143.8   193.3  5551.2  193.05
  5983.8   193.1  6013.8   192.6  6033.8   190.8  6043.8   191.1    6060  192.86
  6083.8   192.3  6214.8   194.6  6364.8   192.8  6814.8   192.9  6960.2   194.8
#Mann= 7 ,-1 , 0
  3983.8    .075       0  4516.9     .05       0  4988.2    .045       0
  5008.1     .05       0  5551.2    .075       0    6060    .045       0
  6960.2      .2       0
#XS Ineff= 2 , 0
       0                    5850       0     195
Permanent Ineff=
       F       F
Bank Sta=4988.2,5008.1
XS Rating Curve= 0
Exp/Cntr=.3,.1

Type RM Length L Ch R = 1 ,4853.0  ,121.4,127.7,116.7
BEGIN DESCRIPTION:
Cross Section XS11
END DESCRIPTION:
XS GIS Cut Line= 3
    2984778.4362   13940784.7726    2984913.6895   13938383.2375
    2984462.8757   13937415.1611
#Sta/Elev= 30
  3829.3   195.4  3949.3   194.3  4509.3   192.3  4859.3   192.2  4949.3     193
  4987.3  190.93  4993.4  189.23  4995.6  186.23  4997.7  184.81  5000.6  184.51
  5004.3  186.17    5006  188.63  5010.8  190.67  5089.3   192.9  5919.3   192.5
  6009.3   192.2  6019.3   191.1  6029.3   190.8  6039.3   191.9  6056.7  191.85
  6069.3   191.4  6089.3   192.1  6284.6     192  6314.6     191  6344.6   192.1
  6764.6   192.2  6894.6   193.1  6914.6   192.6  7044.6   192.6  7302.5   195.5
#Mann= 5 ,-1 , 0
  3829.3    .075       0  4987.3    .045       0  5010.8    .075       0
  6056.7    .045       0  7302.5      .2       0
#XS Ineff= 2 , 0
       0                    5850       0   195.4
Permanent Ineff=
       F       F
Bank Sta=4987.3,5010.8
XS Rating Curve= 0
Exp/Cntr=.5,.3

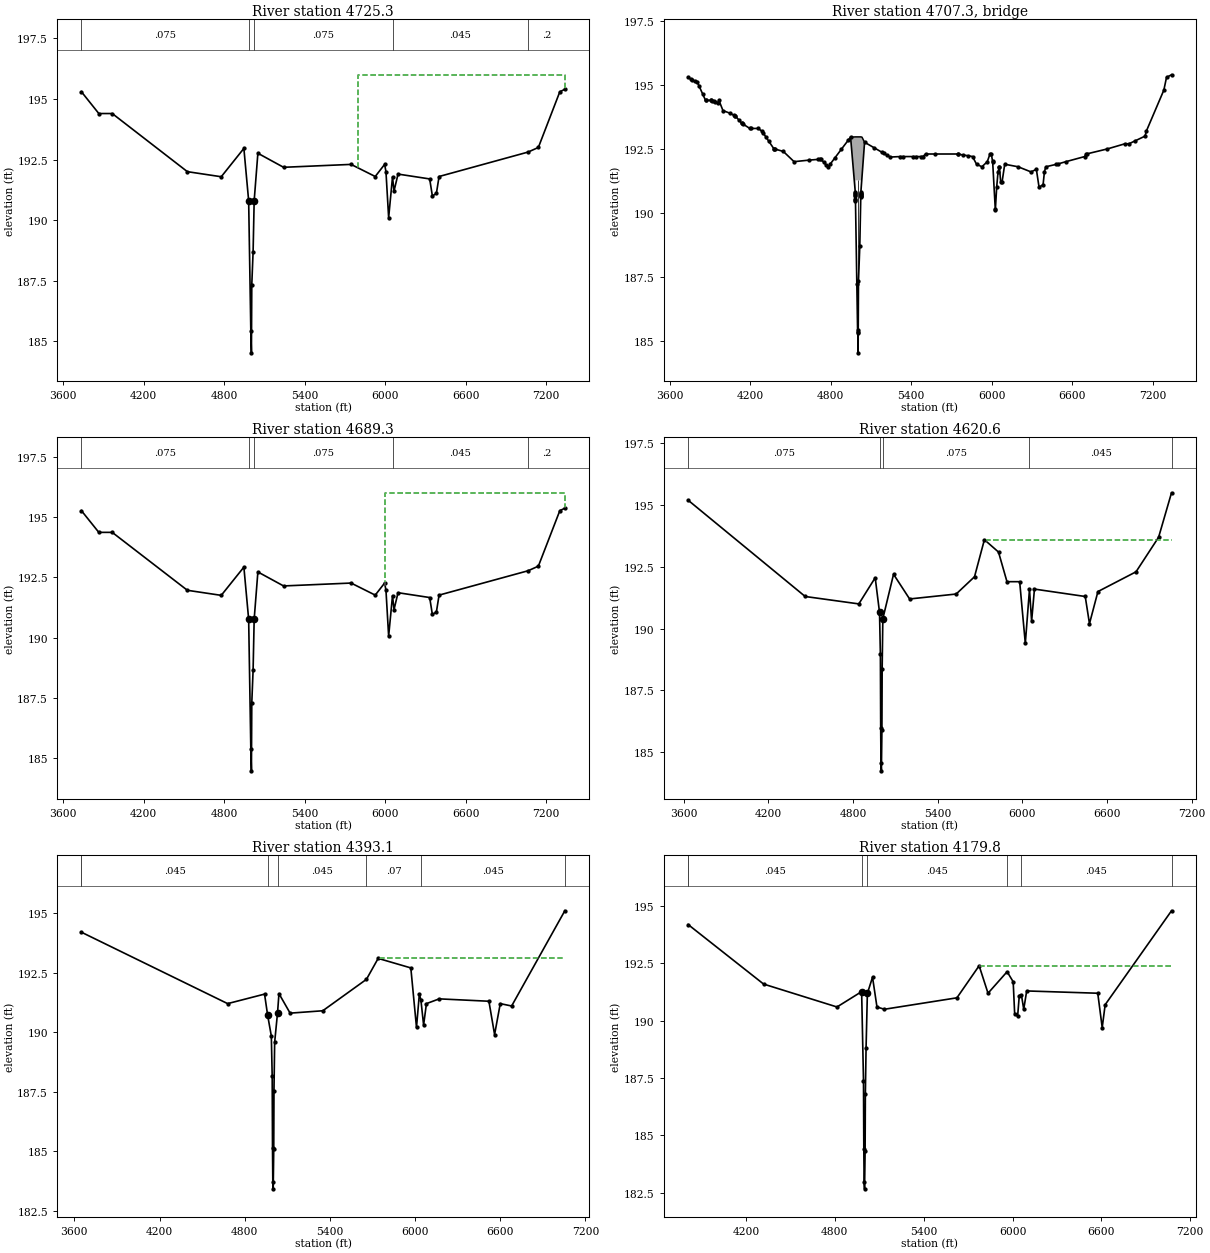
Type RM Length L Ch R = 1 ,4725.3  ,36,36,36
BEGIN DESCRIPTION:
Upstream Section of Bridge/Culvert/Weir
END DESCRIPTION:
XS GIS Cut Line= 3
    2984902.2445   13940878.7175    2985025.8625   13938365.8293
    2984575.6757   13937376.5566
#Sta/Elev= 30
  3736.5   195.3  3866.3   194.4  3966.3   194.4  4526.3     192  4778.7  191.79
  4947.4  192.96    4983   190.8  4999.1  185.43  5003.6  184.52  5006.3  187.33
  5016.1  188.69  5024.1   190.8  5051.7  192.76  5243.2  192.18  5746.3   192.3
  5926.3   191.8  5996.3   192.3  6006.3     192  6026.3   190.1  6055.1  191.78
  6066.3   191.2  6096.3   191.9  6332.1   191.7  6352.1     191  6382.1   191.1
  6402.1   191.8  7065.9  192.81  7142.1     193  7302.1   195.3  7339.3   195.4
#Mann= 5 ,-1 , 0
  3736.5    .075       0    4983    .045       0  5024.1    .075       0
  6055.1    .045       0  7065.9      .2       0
#XS Ineff= 2 ,-1
    4500    4950   191.8    5800    7500     196
Permanent Ineff=
       F       F
Bank Sta=4983,5024.1
XS Rating Curve= 0
Exp/Cntr=.5,.3

Type RM Length L Ch R = 3 ,4707.3  ,,,
BEGIN DESCRIPTION:
McGEE ROAD
Structure ID: L114-01-00-S3
END DESCRIPTION:
Bridge Culvert--1,0,-1,-1, 0
Deck Dist Width WeirC Skew NumUp NumDn MinLoCord MaxHiCord MaxSubmerge Is_Ogee
10,16,2.6,0, 19, 19, , , .95, 0, 1,1,,
  4947.4    4983  4983.1 4983.21  4983.3  4983.4 4983.79  4983.9 4984.01  4993.8
  4999.1    5000    5001  5003.6  5006.3  5016.1  5023.9  5032.4  5051.7
  192.96  192.97  192.97  192.97  192.97  192.97  192.97  192.97  192.97  192.97
  192.97  192.97  192.97  192.97  192.97  192.97  192.97  192.96  192.76
           190.8  191.27  191.27  191.27  191.27  191.27  191.27  191.27  191.27
  191.27  191.27  191.27  191.27  191.27  191.27  191.27
  4947.4    4983  4983.1 4983.21  4983.3  4983.4 4983.79  4983.9 4984.01  4993.8
  4999.1    5000    5001  5003.6  5006.3  5016.1  5023.9  5032.4  5051.7
  192.92  192.97  192.97  192.97  192.97  192.97  192.97  192.97  192.97  192.97
  192.97  192.97  192.97  192.97  192.97  192.97  192.97  192.96  192.72
           190.8  191.27  191.27  191.27  191.27  191.27  191.27  191.27  191.27
  191.27  191.27  191.27  191.27  191.27  191.27  191.27
Pier Skew, UpSta & Num, DnSta & Num=  ,5003.6, 2 ,5003.6, 2 , 0 , 0 , 0 ,,
     1.2     1.2
  183.71  192.14
     1.2     1.2
  183.71  192.14
BR Coef= 1 , 0 , 0 ,1.25, 0 ,,,.8,-1,2,1,
WSPro=,,,, 1 ,,,, 0 ,,,, 0 ,,,,-1 ,-1 ,-1 , 0 , 0 , 0 , 0 , 0
BR U #Sta/Elev= 129
  3736.5   195.3  3756.5  195.23  3766.3   195.2  3786.5  195.15  3806.3   195.1
  3816.5  194.98  3846.5  194.63  3866.3   194.4  3866.5   194.4  3906.3   194.4
  3906.5   194.4  3916.5  194.38  3926.5  194.36  3936.5  194.34  3956.3   194.3
  3966.3   194.4  3996.3     194  4046.3   193.9  4076.5  193.82  4086.3   193.8
  4086.5   193.8  4116.5  193.62  4136.3   193.5  4136.5   193.5  4146.5  193.47
  4196.3   193.3  4206.5   193.3  4256.3   193.3  4286.3   193.2  4296.5  193.12
  4316.5  192.97  4336.5  192.81  4376.3   192.5  4376.5   192.5  4386.5  192.49
  4446.3   192.4  4526.3     192  4636.5  192.06  4706.5  192.09  4716.5   192.1
  4726.3   192.1  4746.5  191.98  4766.5  191.86  4778.7  191.79  4796.5  191.91
    4829  192.14  4879.4  192.49  4928.7  192.83  4947.4  192.96    4983   190.8
  4983.1  190.77 4983.21  190.73  4983.3   190.7  4983.4  190.67 4983.79  190.54
  4983.9   190.5 4984.01  190.46  4993.8   187.2  4999.1  185.43    5000  185.31
    5001  185.35  5003.6  184.52  5006.3  187.33  5016.1  188.69 5023.39  190.61
  5023.5  190.64 5023.61  190.67  5023.7  190.69 5023.79  190.72  5023.9  190.75
    5024  190.77  5024.1   190.8  5051.7  192.76    5124  192.54  5179.6  192.37
  5195.9  192.32  5215.9  192.26  5243.2  192.18  5315.9   192.2  5336.3   192.2
  5415.9   192.2  5436.3   192.2  5475.9   192.2  5486.3   192.2  5506.3   192.3
  5576.3   192.3  5745.9   192.3  5746.3   192.3  5785.9  192.26  5825.9  192.23
  5856.3   192.2  5886.3   191.9  5926.3   191.8  5966.3     192  5986.3   192.3
  5996.3   192.3  6005.9  192.01  6006.3     192  6025.9  190.14  6026.3   190.1
  6036.3     191  6046.3   191.6  6055.1  191.78  6056.3   191.8  6066.3   191.2
  6076.3   191.2  6096.3   191.9  6196.3   191.8  6292.1   191.6  6332.1   191.7
  6352.1     191  6382.1   191.1  6392.1   191.6  6402.1   191.8  6482.1   191.9
  6492.3  191.91  6552.3     192  6692.1   192.2  6702.1   192.3  6712.3  192.31
  6862.1   192.5  6992.1   192.7  7022.1   192.7  7065.9  192.81  7142.1     193
  7152.1   193.2  7282.1   194.8  7302.1   195.3  7339.3   195.4
BR U #Mann= 5
  3736.5     .07    4983    .044  5024.1     .07  6055.1    .045  7065.9      .2
BR D #Sta/Elev= 129
  3736.5  195.26  3756.5  195.19  3766.3  195.16  3786.5  195.11  3806.3  195.06
  3816.5  194.94  3846.5  194.59  3866.3  194.36  3866.5  194.36  3906.3  194.36
  3906.5  194.36  3916.5  194.34  3926.5  194.32  3936.5   194.3  3956.3  194.26
  3966.3  194.36  3996.3  193.96  4046.3  193.86  4076.5  193.78  4086.3  193.76
  4086.5  193.76  4116.5  193.58  4136.3  193.46  4136.5  193.46  4146.5  193.43
  4196.3  193.26  4206.5  193.26  4256.3  193.26  4286.3  193.16  4296.5  193.08
  4316.5  192.93  4336.5  192.77  4376.3  192.46  4376.5  192.46  4386.5  192.45
  4446.3  192.36  4526.3  191.96  4636.5  192.02  4706.5  192.05  4716.5  192.06
  4726.3  192.06  4746.5  191.94  4766.5  191.82  4778.7  191.75  4796.5  191.87
    4829   192.1  4879.4  192.45  4928.7  192.79  4947.4  192.92    4983  190.76
  4983.1  190.73 4983.21  190.69  4983.3  190.66  4983.4  190.63 4983.79   190.5
  4983.9  190.46 4984.01  190.42  4993.8  187.16  4999.1  185.39    5000  185.27
    5001  185.31  5003.6  184.48  5006.3  187.29  5016.1  188.65 5023.39  190.57
  5023.5   190.6 5023.61  190.63  5023.7  190.65 5023.79  190.68  5023.9  190.71
    5024  190.73  5024.1  190.76  5051.7  192.72    5124   192.5  5179.6  192.33
  5195.9  192.28  5215.9  192.22  5243.2  192.14  5315.9  192.16  5336.3  192.16
  5415.9  192.16  5436.3  192.16  5475.9  192.16  5486.3  192.16  5506.3  192.26
  5576.3  192.26  5745.9  192.26  5746.3  192.26  5785.9  192.22  5825.9  192.19
  5856.3  192.16  5886.3  191.86  5926.3  191.76  5966.3  191.96  5986.3  192.26
  5996.3  192.26  6005.9  191.97  6006.3  191.96  6025.9   190.1  6026.3  190.06
  6036.3  190.96  6046.3  191.56  6055.1  191.74  6056.3  191.76  6066.3  191.16
  6076.3  191.16  6096.3  191.86  6196.3  191.76  6292.1  191.56  6332.1  191.66
  6352.1  190.96  6382.1  191.06  6392.1  191.56  6402.1  191.76  6482.1  191.86
  6492.3  191.87  6552.3  191.96  6692.1  192.16  6702.1  192.26  6712.3  192.27
  6862.1  192.46  6992.1  192.66  7022.1  192.66  7065.9  192.77  7142.1  192.96
  7152.1  193.16  7282.1  194.76  7302.1  195.26  7339.3  195.36
BR D #Mann= 5
  3736.5     .07    4983    .044  5024.1     .07  6055.1    .045  7065.9      .2
BC Design=,, 0 ,, 0 ,,,,,,
BC HTab HWMax=195.4

Type RM Length L Ch R = 1 ,4689.3  ,77.1,68.7,52.3
BEGIN DESCRIPTION:
Downstream Section of Bridge/Culvert/Weir
END DESCRIPTION:
XS GIS Cut Line= 4
    2984932.0654   13940876.9529    2985007.6989   13939620.7838
    2985057.6287   13938545.5792    2985116.4482   13937278.9391
#Sta/Elev= 30
  3736.5  195.26  3866.3  194.36  3966.3  194.36  4526.3  191.96  4778.7  191.75
  4947.4  192.92    4983  190.76  4999.1  185.39  5003.6  184.48  5006.3  187.29
  5016.1  188.65  5024.1  190.76  5051.7  192.72  5243.2  192.14  5746.3  192.26
  5926.3  191.76  5996.3  192.26  6006.3  191.96  6026.3  190.06  6055.1  191.74
  6066.3  191.16  6096.3  191.86  6332.1  191.66  6352.1  190.96  6382.1  191.06
  6402.1  191.76  7065.9  192.77  7142.1  192.96  7302.1  195.26  7339.3  195.36
#Mann= 5 ,-1 , 0
  3736.5    .075       0    4983    .045       0  5024.1    .075       0
  6055.1    .045       0  7065.9      .2       0
#XS Ineff= 2 ,-1
    4500    4950   191.7    6000    7500     196
Permanent Ineff=
       F       F
Bank Sta=4983,5024.1
XS Rating Curve= 0
Exp/Cntr=.5,.3

Type RM Length L Ch R = 1 ,4620.6  ,230.1,227.5,216.1
BEGIN DESCRIPTION:
Cross Section XS10
END DESCRIPTION:
XS GIS Cut Line= 3
    2985053.4452   13940983.4212    2985094.6342   13938549.0234
     2985111.406   13937557.7579
#Sta/Elev= 30
  3630.6   195.2  4460.6   191.3  4840.6     191  4956.7  192.06  4987.3  190.66
  4993.4  188.96  4995.6  185.96  4997.7  184.54  5000.6  184.24  5004.3   185.9
    5006  188.36  5010.8   190.4  5086.7   192.2  5200.6   191.2  5530.6   191.4
  5660.6   192.1  5730.6   193.6  5830.6   193.1  5890.6   191.9  5980.6   191.9
  6020.6   189.4  6050.2  191.59  6065.3   190.3  6085.3   191.6  6445.3   191.3
  6475.3   190.2  6535.3   191.5  6805.3   192.3  6965.3   193.7  7056.8   195.5
#Mann= 5 ,-1 , 0
  3630.6    .075       0  4987.3    .045       0  5010.8    .075       0
  6050.2    .045       0  7056.8      .2       0
#XS Ineff= 2 , 0
       0                    5750       0   193.6
Permanent Ineff=
       F       F
Bank Sta=4987.3,5010.8
XS Rating Curve= 0
Exp/Cntr=.3,.1

Type RM Length L Ch R = 1 ,4393.1  ,264,213.3,91.3
BEGIN DESCRIPTION:
Cross Section XS09
END DESCRIPTION:
XS GIS Cut Line= 4
    2985305.4017   13940955.8635    2985301.6541   13938955.6658
    2985167.5325    13937628.988     2985160.366   13937558.0998
#Sta/Elev= 30
  3649.6   194.2  4679.6   191.2  4939.6   191.6  4961.1  190.72  4987.3  189.84
  4993.4  188.14  4995.6  185.14  4997.7  183.72  5000.6  183.42  5004.3  185.08
    5006  187.54  5010.8  189.58  5031.1  190.82  5041.1  191.62  5119.6   190.8
  5349.6   190.9  5657.2  192.22  5739.8   193.1  5969.8   192.7  6009.8   190.2
  6029.8   191.6  6040.5  191.37  6059.8   190.3  6079.8   191.2  6169.8   191.4
  6519.8   191.3  6559.8   189.9  6599.8   191.2  6679.8   191.1  7054.5   195.1
#Mann= 7 , 1 , 0
  3649.6      .2       0  3649.6    .045       0  4961.1    .045       0
  5031.1    .045       0  5657.2     .07       0  6040.5    .045       0
  7054.5      .2       0
#XS Ineff= 2 , 0
       0                    5750       0   193.1
Permanent Ineff=
       F       F
Bank Sta=4961.1,5031.1
XS Rating Curve= 0
Exp/Cntr=.3,.1

Type RM Length L Ch R = 1 ,4179.8  ,349.3,268.4,54.7
BEGIN DESCRIPTION:
Cross Section XS8.5
END DESCRIPTION:
XS GIS Cut Line= 6
    2985823.3471   13940754.4523    2985556.5427   13939784.8462
    2985296.3063   13938591.7409      2985213.33   13937727.1185
    2985204.5707   13937635.8456    2985197.1343   13937558.3566
#Sta/Elev= 30
  3808.8   194.2  4318.8   191.6  4814.4   190.6  4980.8  191.27  4993.4  187.38
  4995.6  184.38  4997.7  182.96  5000.6  182.66  5004.3  184.32    5006  186.78
  5010.8  188.82  5019.6  191.19  5054.4   191.9  5084.4   190.6  5134.4   190.5
  5624.4     191  5774.4   192.4  5834.4   191.2  5963.4  192.14  6004.4   191.7
  6014.4   190.3  6034.4   190.2  6045.6   191.1  6059.9  191.13  6075.6   190.5
  6095.6   191.3  6575.6   191.2  6605.6   189.7  6625.6   190.7  7073.7   194.8
#Mann= 7 , 1 , 0
  3808.8      .2       0  3808.8    .045       0  4980.8    .045       0
  5019.6    .045       0  5963.4    .065       0  6059.9    .045       0
  7073.7      .2       0
#XS Ineff= 2 , 0
       0                    5775       0   192.4
Permanent Ineff=
       F       F
Bank Sta=4980.8,5019.6
XS Rating Curve= 0
Exp/Cntr=.3,.1