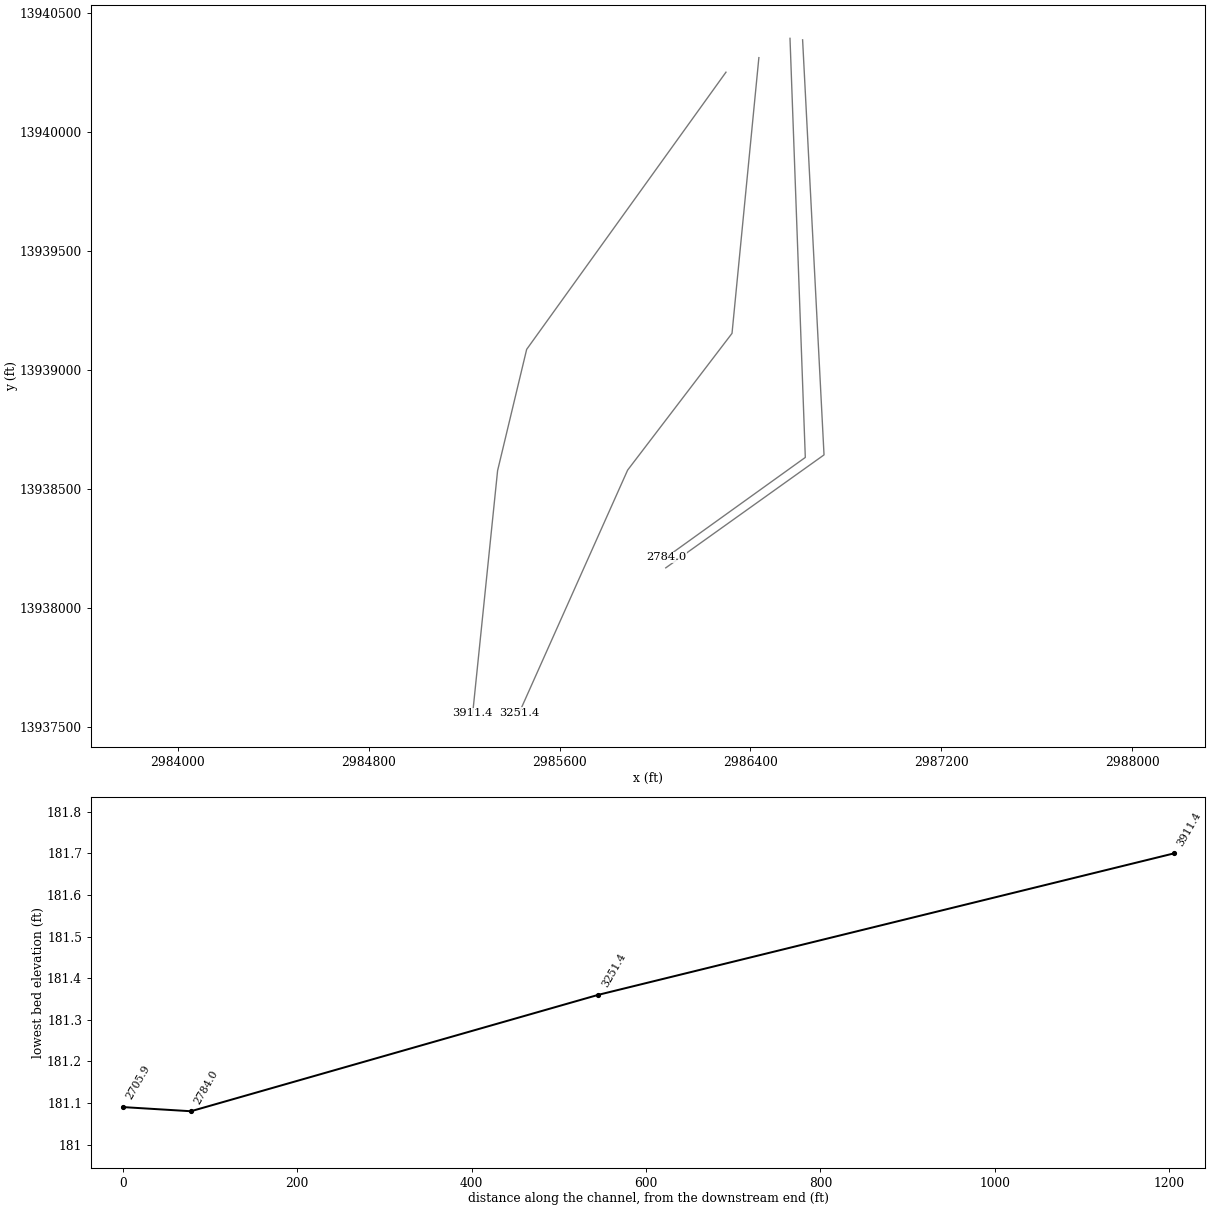
HEC-RAS study L114-01-00.PRJ: L114-01-00

--- L114-01-00.g01 (geometry) --- (continued)

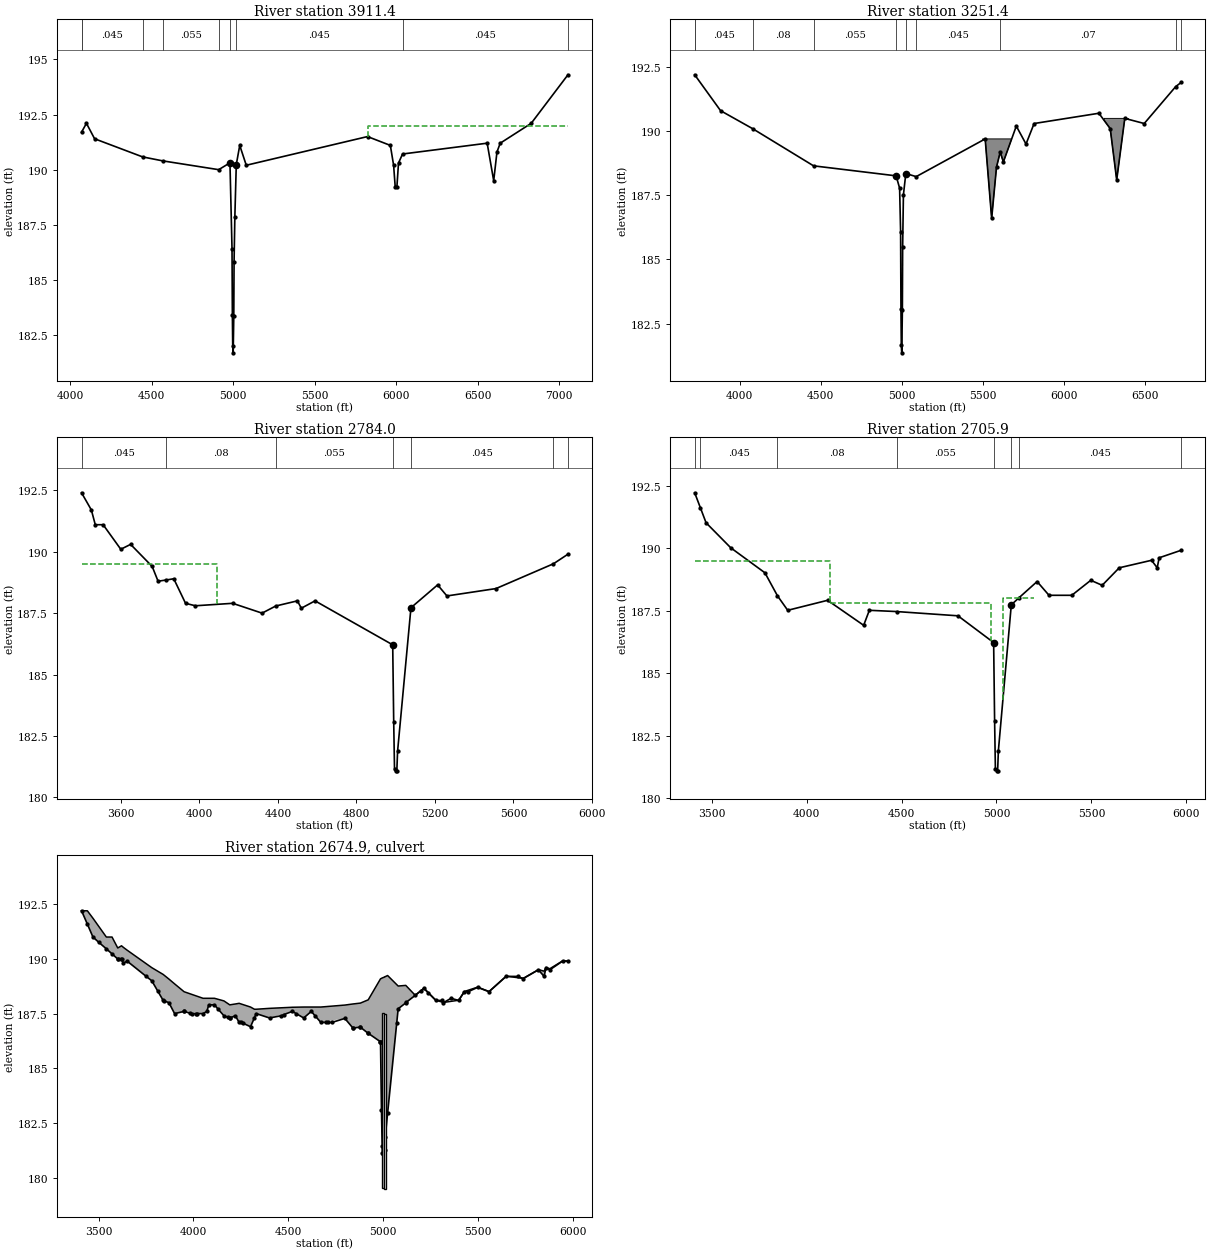
Type RM Length L Ch R = 1 ,3911.4  ,568.5,660,660.3
BEGIN DESCRIPTION:
Cross Section XS08
END DESCRIPTION:
XS GIS Cut Line= 5
    2986297.6208   13940252.7388     2985461.947   13939088.0325
    2985340.1114   13938578.6594    2985244.3053   13937643.2024
    2985235.6432   13937558.6255
#Sta/Elev= 30
  4070.8   191.7  4100.8   192.1  4150.8   191.4  4444.8  190.58  4567.6   190.4
  4911.7     190  4980.8  190.31  4993.4  186.42  4995.6  183.42  4997.7     182
  5000.6   181.7  5004.3  183.36    5006  185.82  5010.8  187.86  5019.6  190.23
  5040.8   191.1  5080.8   190.2  5824.3   191.5  5964.3   191.1  5984.3   190.2
  5994.3   189.2  6004.3   189.2  6014.3   190.3  6039.1  190.71    6558   191.2
    6598   189.5    6618   190.8    6638   191.2    6828   192.1  7053.4   194.3
#Mann= 9 , 1 , 0
  4070.8      .2       0  4070.8    .045       0  4444.8     .08       0
  4567.6    .055       0  4911.7    .045       0  4980.8    .045       0
  5019.6    .045       0  6039.1    .045       0  7053.4      .2       0
#XS Ineff= 2 , 0
       0                    5825       0     192
Permanent Ineff=
       F       F
Bank Sta=4980.8,5019.6
XS Rating Curve= 0
Exp/Cntr=.3,.1

Type RM Length L Ch R = 1 ,3251.4  ,313.7,467.4,558.9
BEGIN DESCRIPTION:
Cross Section XS07
END DESCRIPTION:
XS GIS Cut Line= 4
     2986435.567   13940313.8218    2986322.9558   13939155.3052
    2985885.2931   13938580.7673    2985430.1536   13937559.9837
#Sta/Elev= 30
  3721.7   192.2  3881.7   190.8  4079.4   190.1  4455.8  188.65  4965.6  188.26
  4987.3  187.78  4993.4  186.08  4995.6  183.08  4997.7  181.66  5000.6  181.36
  5004.3  183.02    5006  185.48  5010.8  187.52  5025.6  188.35  5089.7  188.23
  5515.7   189.7  5555.7   186.6  5585.7   188.6  5608.6  189.19  5627.9   188.8
  5707.9   190.2  5767.9   189.5  5817.9   190.3  6217.9   190.7  6287.9   190.1
  6327.9   188.1  6377.9   190.5  6497.9   190.3  6692.4  191.74  6725.6   191.9
#Mann= 10 , 1 , 0
  3721.7      .2       0  3721.7    .045       0  4079.4     .08       0
  4455.8    .055       0  4965.6    .045       0  5025.6    .055       0
  5089.7    .045       0  5608.6     .07       0  6692.4    .045       0
  6725.6      .2       0
#Block Obstruct= 2 ,-1
    5500    5700   189.7    6250    6400   190.5
Bank Sta=4965.6,5025.6
XS Rating Curve= 0
Exp/Cntr=.3,.1

Type RM Length L Ch R = 1 ,2784.0  ,104.8,78.1,44.5
BEGIN DESCRIPTION:
Left  Ineffective used to transition with downstream cross sections
Cross Section XS06
END DESCRIPTION:
XS GIS Cut Line= 3
     2986566.066   13940394.9213    2986630.2555   13938634.0255
     2986048.299   13938215.2817
#Sta/Elev= 30
  3399.2   192.4  3449.2   191.7  3469.2   191.1  3509.2   191.1  3599.2   190.1
  3649.2   190.3  3759.2   189.4  3789.2   188.8  3831.5  188.85  3869.2   188.9
  3929.2   187.9  3979.2   187.8  4169.2   187.9  4319.2   187.5  4388.8  187.79
  4499.2     188  4519.2   187.7  4589.2     188    4985  186.21  4990.1  183.08
  4994.2  181.15  5000.3  181.08    5006  181.08  5009.9  181.88    5078  187.72
  5213.9  188.65  5261.3   188.2  5511.3   188.5  5804.3  189.51  5878.2   189.9
#Mann= 7 ,-1 , 0
  3399.2    .045       0  3831.5     .08       0  4388.8    .055       0
    4985    .045       0    5078    .045       0  5804.3     .07       0
  5878.2      .2       0
#XS Ineff= 2 , 0
       0    4090   189.5               0
Permanent Ineff=
       F       F
Bank Sta=4985,5078
XS Rating Curve= 0
Exp/Cntr=.5,.3

Type RM Length L Ch R = 1 ,2705.9  ,83.7,62,47.7
BEGIN DESCRIPTION:
Upstream Section of Bridge/Culvert/Weir
Left  Ineffective used to transition with downstream cross section
END DESCRIPTION:
XS GIS Cut Line= 3
    2986618.8995   13940388.5813     2986708.726    13938644.726
    2986045.1874   13938170.0978
#Sta/Elev= 30
  3410.4  192.21    3441   191.6  3470.4  191.01  3600.4  190.01  3780.4  189.01
  3846.4  188.09  3900.4  187.51  4110.4  187.91  4300.4  186.91  4330.4  187.51
  4474.1  187.46  4797.1  187.29    4985  186.22  4990.1  183.09  4994.2  181.16
  5000.3  181.09    5006  181.09  5009.9  181.89    5078  187.73  5119.7  188.02
  5213.9  188.66  5276.6  188.11  5396.6  188.11  5496.6  188.71  5556.6  188.51
  5646.6  189.21  5816.6  189.51  5846.6  189.21  5856.6  189.61  5972.3  189.91
#Mann= 8 ,-1 , 0
  3410.4      .2       0    3441    .045       0  3846.4     .08       0
  4474.1    .055       0    4985    .055       0    5078    .055       0
  5119.7    .045       0  5972.3      .2       0
#XS Ineff= 3 ,-1
    3410    4124   189.5    4125  4971.1   187.8  5033.6    5200     188
Permanent Ineff=
       F       F       F
Bank Sta=4985,5078
XS Rating Curve= 0
Exp/Cntr=.5,.3

Type RM Length L Ch R = 2 ,2674.9  ,,,
BEGIN DESCRIPTION:
BAUER ROAD
Structure ID: L114-01-00-S2
END DESCRIPTION:
Bridge Culvert--1,0,-1,-1, 0
Deck Dist Width WeirC Skew NumUp NumDn MinLoCord MaxHiCord MaxSubmerge Is_Ogee
10,42,3,0, 60, 60, , , .95, 0, 1,1,,
  3410.4    3441  3470.4    3541    3571    3601    3621  3630.4  3650.4  3780.4
  3840.4  3870.4  3900.4  3950.4  4050.4  4070.4  4080.4  4110.4  4160.4    4191
  4220.4  4240.4  4300.4    4321  4330.4  4400.4  4520.4  4580.4  4620.4  4670.4
  4797.1  4839.4  4878.9  4920.3    4985  4990.1  4993.8  4994.2    5006  5006.3
  5009.9  5022.5    5078    5118  5167.5  5213.9  5276.6  5316.6  5396.6  5426.6
  5496.6  5556.6  5646.6  5736.6  5816.6  5846.6  5856.6  5876.6  5944.1  5972.3
   192.2   192.2  191.86     191     191   190.5   190.6  190.53   190.4   189.6
  189.29  189.08  188.86   188.5   188.2   188.2   188.2   188.2  188.08   187.9
  187.94  187.97   187.8   187.7   187.7  187.74  187.79   187.8   187.8   187.8
  187.89  187.94  187.98  188.13  189.09  189.11  189.13  189.13  189.17  189.18
  189.19  189.24  188.76  188.79  188.34  188.66  188.11  188.01  188.11  188.51
  188.71  188.51  189.21  189.11  189.51  189.44  189.61  189.55  189.91   189.9
   192.2  191.59     191  190.46  190.23     190  189.99   189.8   189.9     189
   188.1     188   187.5   187.6   187.5   187.6   187.9   187.9   187.4   187.3
   187.4   187.1   186.9  187.31   187.5   187.3   187.6   187.3   187.6   187.1
  187.28  186.84  186.88   186.6  186.21  183.08  181.44  181.15  181.08  181.26
  181.88  182.96  187.72  187.99  188.33  188.65   188.1     188   188.1   188.5
   188.7   188.5   189.2   189.1   189.5   189.2   189.6   189.5   189.9   189.9
  3410.4    3441  3470.4    3541    3571    3601    3621  3630.4  3650.4  3780.4
  3840.4  3870.4  3900.4  3950.4  4050.4  4070.4  4080.4  4110.4  4160.4    4191
  4220.4  4240.4  4300.4    4321  4330.4  4400.4  4520.4  4580.4  4620.4  4670.4
  4797.1  4839.4  4878.9  4920.3    4985  4990.1  4993.8  4994.2    5006  5006.3
  5009.9  5022.5    5078    5118  5167.5  5213.9  5276.6  5316.6  5396.6  5426.6
  5496.6  5556.6  5646.6  5736.6  5816.6  5846.6  5856.6  5876.6  5944.1  5972.3
   192.2   192.2  191.86     191     191   190.5   190.6  190.53   190.4   189.6
  189.29  189.08  188.86   188.5   188.2   188.2   188.2   188.2  188.08   187.9
  187.94  187.97   187.8   187.7   187.7  187.74  187.79   187.8   187.8   187.8
  187.89  187.94  187.98  188.13  189.09  189.11  189.13  189.13  189.17  189.18
  189.19  189.24  188.76  188.79  188.34  188.66  188.11  188.01  188.11  188.51
  188.71  188.51  189.21  189.11  189.51  189.44  189.61  189.55  189.91   189.9
  192.09  191.48  190.89  190.35  190.12  189.89  189.88  189.69  189.79  188.89
  187.99  187.89  187.39  187.49  187.39  187.49  187.79  187.79  187.29  187.19
  187.29  186.99  186.79   187.2  187.39  187.19  187.49  187.19  187.49  186.99
  187.17  186.73  186.77  186.49   186.1  182.97  181.33  181.04  180.97  181.15
  181.77  182.85  187.61  187.88  188.22  188.54  187.99  187.89  187.99  188.39
  188.59  188.39  189.09  188.99  189.39  189.09  189.49  189.39  189.79  189.79
BR Coef= 1 , 0 , 0 ,1.25, 0 ,,,.8,-1,2,0,
WSPro=,,,, 1 ,,,, 0 ,,,, 0 ,,,,-1 ,-1 ,-1 , 0 , 0 , 0 , 0 , 0
Culvert=2,8,10,42,.02,.5,1,8,1,179.55,4996.1,179.4,4996.1,Culvert #1  , 0 ,10
Culvert Bottom n=.02
Culvert=2,8,10,42,.02,.5,1,8,1,179.49,5008.6,179.44,5008.6,Culvert #2  , 0 ,10
Culvert Bottom n=.02
BR U #Sta/Elev= 97
  3410.4   192.2    3441  191.59  3470.4     191    3501  190.76    3541  190.46
    3571  190.23  3600.4     190    3601     190  3620.4     190    3621  189.99
  3630.4   189.8  3650.4   189.9    3751   189.2  3780.4     189    3811  188.54
  3840.4   188.1  3846.4  188.08  3870.4     188  3900.4   187.5  3950.4   187.6
    3951   187.6    3981  187.52  3990.4   187.5    4011   187.5    4021   187.5
  4050.4   187.5  4070.4   187.6  4080.4   187.9  4110.4   187.9    4131  187.69
  4160.4   187.4    4181  187.33  4190.4   187.3    4191   187.3  4220.4   187.4
  4240.4   187.1  4250.4   187.1    4261  187.06  4300.4   186.9    4321  187.31
  4330.4   187.5  4400.4   187.3  4460.4   187.4  4474.1  187.45  4520.4   187.6
    4541   187.5  4580.4   187.3  4620.4   187.6  4640.4   187.4  4670.4   187.1
  4700.4   187.1    4711   187.1  4730.4   187.1  4797.1  187.28  4838.7  186.85
  4839.4  186.84  4877.7  186.88  4878.9  186.88  4919.7   186.6  4920.3   186.6
  4983.6  186.22  4984.9  186.21    4985  186.21  4990.1  183.08  4993.8  181.44
  4994.2  181.15  5000.3  181.08    5006  181.08  5006.3  181.26  5009.9  181.88
  5022.5  182.96  5070.3  187.06    5078  187.72    5118  187.99  5119.7  188.01
  5167.5  188.33  5197.5  188.54  5213.9  188.65  5237.5  188.44  5276.6   188.1
  5306.6   188.1  5316.6     188  5356.6   188.2  5396.6   188.1  5426.6   188.5
  5446.6   188.5  5496.6   188.7  5556.6   188.5  5646.6   189.2  5706.6   189.2
  5736.6   189.1  5816.6   189.5  5846.6   189.2  5856.6   189.6  5876.6   189.5
  5944.1   189.9  5972.3   189.9
BR U #Mann= 8
  3410.4      .2    3441     .04  3846.4    .065  4474.1     .05    4985     .05
    5078     .05  5119.7     .04  5972.3      .2
BR U Banks=4985,5078
BR D #Sta/Elev= 97
  3410.4  192.09    3441  191.48  3470.4  190.89    3501  190.65    3541  190.35
    3571  190.12  3600.4  189.89    3601  189.89  3620.4  189.89    3621  189.88
  3630.4  189.69  3650.4  189.79    3751  189.09  3780.4  188.89    3811  188.43
  3840.4  187.99  3846.4  187.97  3870.4  187.89  3900.4  187.39  3950.4  187.49
    3951  187.49    3981  187.41  3990.4  187.39    4011  187.39    4021  187.39
  4050.4  187.39  4070.4  187.49  4080.4  187.79  4110.4  187.79    4131  187.58
  4160.4  187.29    4181  187.22  4190.4  187.19    4191  187.19  4220.4  187.29
  4240.4  186.99  4250.4  186.99    4261  186.95  4300.4  186.79    4321   187.2
  4330.4  187.39  4400.4  187.19  4460.4  187.29  4474.1  187.34  4520.4  187.49
    4541  187.39  4580.4  187.19  4620.4  187.49  4640.4  187.29  4670.4  186.99
  4700.4  186.99    4711  186.99  4730.4  186.99  4797.1  187.17  4838.7  186.74
  4839.4  186.73  4877.7  186.77  4878.9  186.77  4919.7  186.49  4920.3  186.49
  4983.6  186.11  4984.9   186.1    4985   186.1  4990.1  182.97  4993.8  181.33
  4994.2  181.04  5000.3  180.97    5006  180.97  5006.3  181.15  5009.9  181.77
  5022.5  182.85  5070.3  186.95    5078  187.61    5118  187.88  5119.7   187.9
  5167.5  188.22  5197.5  188.43  5213.9  188.54  5237.5  188.33  5276.6  187.99
  5306.6  187.99  5316.6  187.89  5356.6  188.09  5396.6  187.99  5426.6  188.39
  5446.6  188.39  5496.6  188.59  5556.6  188.39  5646.6  189.09  5706.6  189.09
  5736.6  188.99  5816.6  189.39  5846.6  189.09  5856.6  189.49  5876.6  189.39
  5944.1  189.79  5972.3  189.79
BR D #Mann= 8
  3410.4      .2    3441     .04  3846.4    .065  4474.1     .05    4985     .05
    5078     .05  5119.7     .04  5972.3      .2
BR D Banks=4985,5078
BC Design=,, 0 ,, 0 ,,,,,,
BC HTab HWMax=192.21