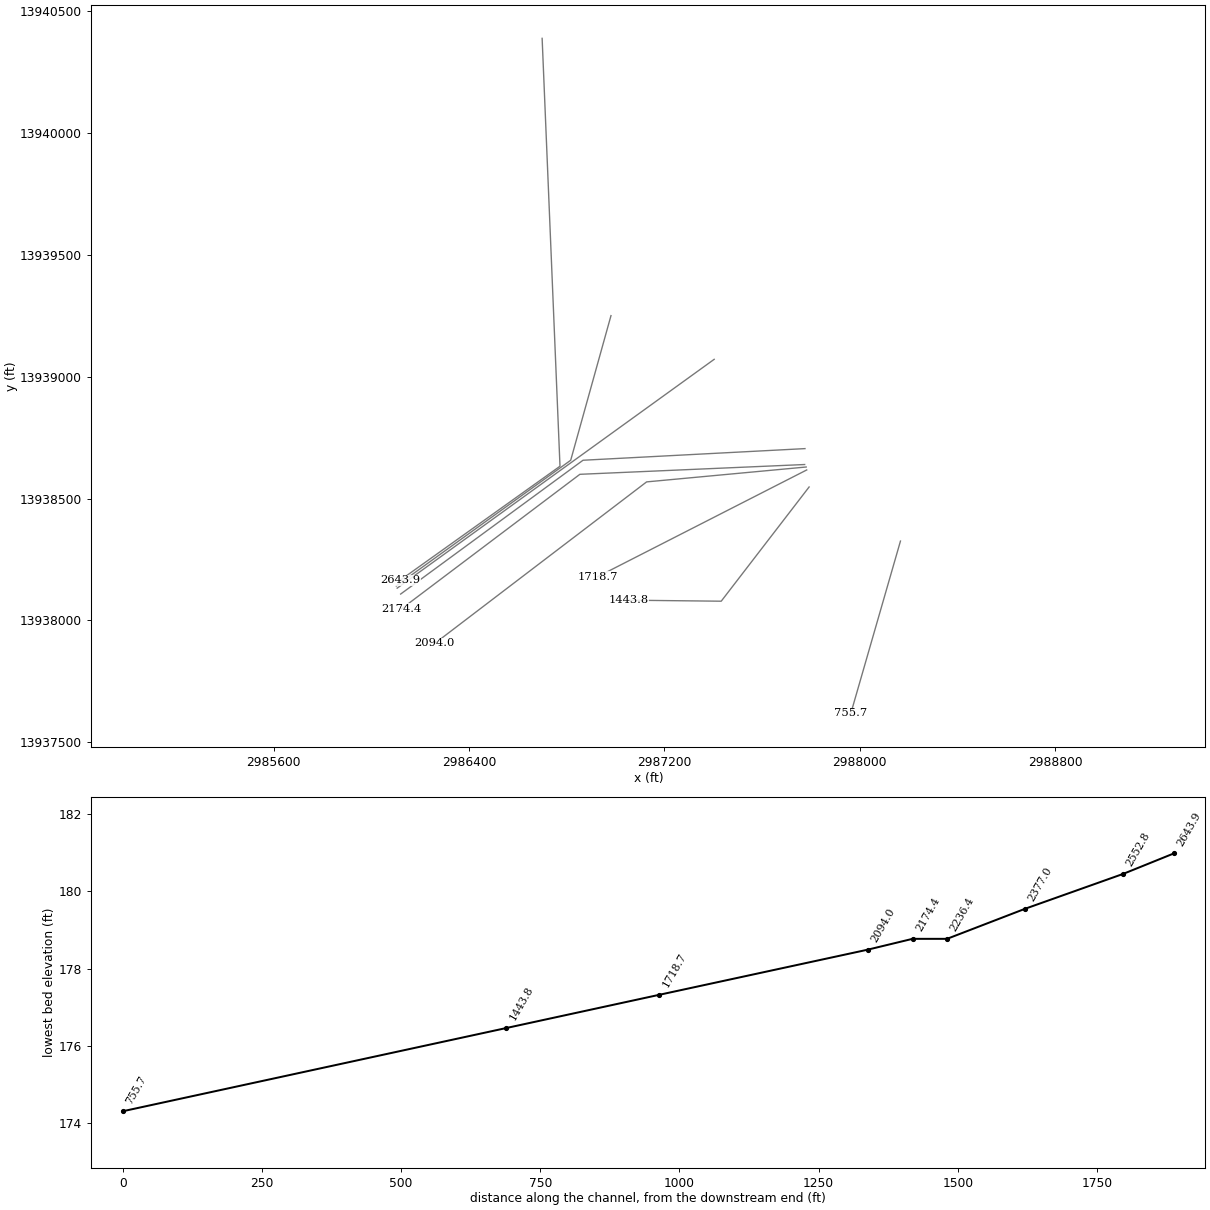
HEC-RAS study L114-01-00.PRJ: L114-01-00

--- L114-01-00.g01 (geometry) --- (continued)

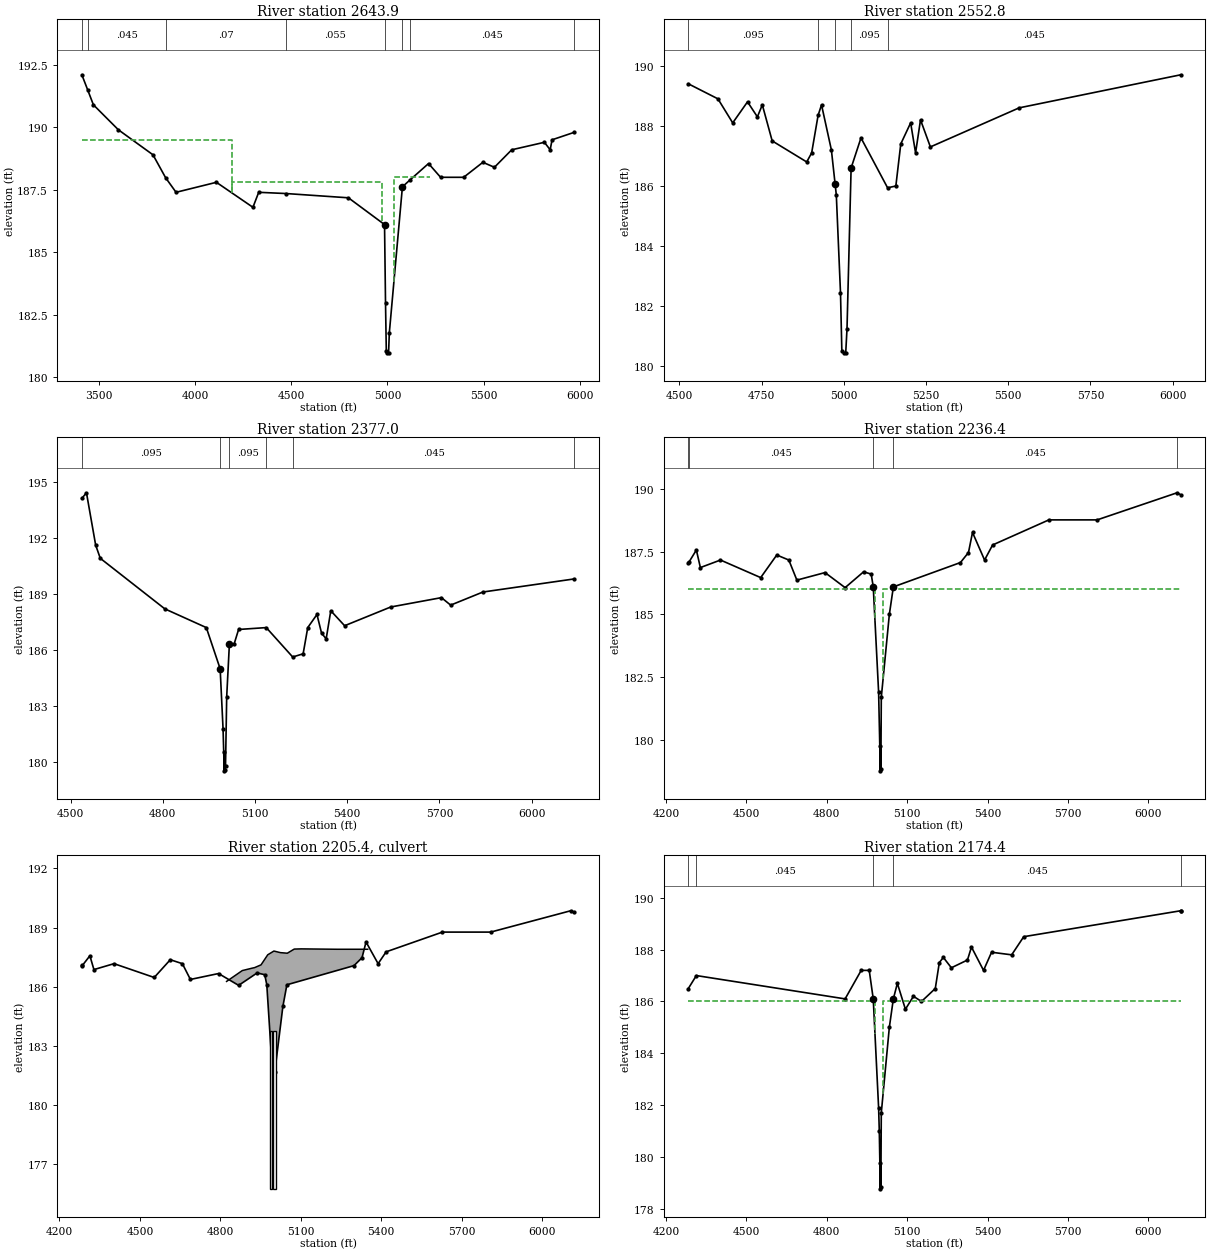
Type RM Length L Ch R = 1 ,2643.9  ,182.6,91.1,8.4
BEGIN DESCRIPTION:
Downstream Section of Bridge/Culvert/Weir
Left  Ineffective used to transition with downstream cross section
END DESCRIPTION:
XS GIS Cut Line= 3
    2986699.4863   13940388.9317    2986772.6568   13938632.6898
     2986118.422   13938165.0725
#Sta/Elev= 30
  3410.4   192.1    3441  191.49  3470.4   190.9  3600.4   189.9  3780.4   188.9
  3846.4  187.98  3900.4   187.4  4110.4   187.8  4300.4   186.8  4330.4   187.4
  4474.1  187.35  4797.1  187.18    4985  186.11  4990.1  182.98  4994.2  181.05
  5000.3  180.98    5006  180.98  5009.9  181.78    5078  187.62  5119.7  187.91
  5213.9  188.55  5276.6     188  5396.6     188  5496.6   188.6  5556.6   188.4
  5646.6   189.1  5816.6   189.4  5846.6   189.1  5856.6   189.5  5972.3   189.8
#Mann= 8 ,-1 , 0
  3410.4      .2       0    3441    .045       0  3846.4     .07       0
  4474.1    .055       0    4985    .055       0    5078    .055       0
  5119.7    .045       0  5972.3      .2       0
#XS Ineff= 3 ,-1
    3410    4190   189.5    4190  4971.1   187.8  5033.6    5220     188
Permanent Ineff=
       F       F       F
Bank Sta=4985,5078
XS Rating Curve= 0
Exp/Cntr=.5,.3

Type RM Length L Ch R = 1 ,2552.8  ,207.6,175.8,10.8
BEGIN DESCRIPTION:
Cross Section XS05
END DESCRIPTION:
XS GIS Cut Line= 3
    2986981.4617   13939250.7368    2986816.4978   13938657.2116
    2986101.9829   13938141.2312
#Sta/Elev= 30
  4527.4   189.4  4617.4   188.9  4662.4   188.1  4707.4   188.8  4737.4   188.3
  4752.4   188.7  4782.4   187.5  4887.4   186.8  4902.4   187.1    4922  188.35
  4932.4   188.7  4962.4   187.2  4973.8  186.06  4977.4   185.7  4990.1  182.45
  4994.2  180.52  5000.3  180.45    5006  180.45  5009.9  181.25  5022.4   186.6
  5052.4   187.6  5133.3  185.94  5158.4     186  5173.4   187.4  5203.4   188.1
  5218.4   187.1  5233.4   188.2  5263.4   187.3  5533.4   188.6  6024.8   189.7
#Mann= 5 ,-1 , 0
  4527.4    .095       0    4922    .055       0  4973.8    .055       0
  5022.4    .095       0  5133.3    .045       0
Bank Sta=4973.8,5022.4
XS Rating Curve= 0
Exp/Cntr=.3,.1

Type RM Length L Ch R = 1 ,2377.0  ,206.2,140.6,26.7
BEGIN DESCRIPTION:
Cross sections extends to limits of Drainage Divide
Cross Section XS04
END DESCRIPTION:
XS GIS Cut Line= 2
      2987404.11   13939071.4739    2986105.8182   13938132.2959
#Sta/Elev= 30
  4536.6   194.1  4551.6   194.4  4581.6   191.6  4596.6   190.9  4806.6   188.2
  4941.6   187.2  4986.6     185  4996.1  181.77  4999.9  179.55    5000  180.53
  5001.9  179.62  5004.1  179.83  5007.9  183.51  5016.6   186.3  5031.6   186.3
  5046.6   187.1  5136.6   187.2  5222.6  185.63  5256.6   185.8  5271.6   187.2
  5301.6   187.9  5316.6   186.9  5331.6   186.6  5346.6   188.1  5391.6   187.3
  5541.6   188.3  5706.6   188.8  5736.6   188.4  5841.6   189.1    6139   189.8
#Mann= 6 ,-1 , 0
  4536.6    .095       0  4986.6    .055       0  5016.6    .095       0
  5136.6    .095       0  5222.6    .045       0    6139      .2       0
Bank Sta=4986.6,5016.6
XS Rating Curve= 0
Exp/Cntr=.5,.3

Type RM Length L Ch R = 1 ,2236.4  ,62,62,62
BEGIN DESCRIPTION:
Upstream Section of Baeur-Hockely Road
Cross sections extends to limits of Drainage Divide
END DESCRIPTION:
XS GIS Cut Line= 3
    2987776.0235   13938705.0016     2986866.975   13938657.2652
    2986120.0386   13938108.0323
#Sta/Elev= 30
  4283.5  187.07  4285.5  187.08  4313.5  187.57  4328.5  186.87  4403.5  187.17
  4553.5  186.47  4613.5  187.37  4658.5  187.17  4688.5  186.37  4793.5  186.67
  4868.5  186.07 4937.37   186.7 4965.85  186.61  4973.5   186.1  4993.5   181.9
  4999.9  178.77    5000  179.75  5001.9  178.84  5003.5   181.7  5033.5     185
  5048.5   186.1  5298.8  187.07  5328.8  187.47  5343.8  188.27  5388.8  187.17
  5418.8  187.77  5628.8  188.77  5808.8  188.77    6107  189.85  6120.9  189.77
#Mann= 5 ,-1 , 0
  4283.5      .2       0  4285.5    .045       0  4973.5    .055       0
  5048.5    .045       0    6107      .2       0
#XS Ineff= 2 , 0
       0    4980     186    5010       0     186
Permanent Ineff=
       F       F
Bank Sta=4973.5,5048.5
XS Rating Curve= 0
Exp/Cntr=.5,.3

Type RM Length L Ch R = 2 ,2205.4  ,,,
BEGIN DESCRIPTION:
BAUER-HOCKLEY
Structure ID: L114-01-00-S1
END DESCRIPTION:
Bridge Culvert--1,0,-1,-1, 0
Deck Dist Width WeirC Skew NumUp NumDn MinLoCord MaxHiCord MaxSubmerge Is_Ogee
10,42,3,0, 13, 13, , , .95, 0, 1,1,,
  4823.5    4882    4918    4928    4952    4977    5000    5024    5050    5076
    5102    5235    5350
  186.27  186.82  186.94  186.97  187.11  187.62  187.81  187.73   187.7  187.91
  187.92   187.9   187.9
                                                                                
                        
  4823.5    4882    4918    4928    4952    4977    5000    5024    5050    5076
    5102    5235    5350
   186.4  186.82  186.94  186.97  187.11  187.62  187.81  187.73   187.7  187.91
  187.92   187.9   187.9
                                                                                
                        
BR Coef= 1 , 0 , 0 ,1.25, 0 ,,,.8,-1,2,0,
WSPro=,,,, 1 ,,,, 0 ,,,, 0 ,,,,-1 ,-1 ,-1 , 0 , 0 , 0 , 0 , 0
Multiple Barrel Culv=2,8,10,42,.02,.4,1,10,1,175.76,175.57, 2,2-10x8 CBC  , 0 ,10
  4989.2  4989.2  5002.3  5002.3
Culvert Bottom n=.02
BC Design=,, 0 ,, 0 ,,,,,,
BC HTab HWMax=189.87

Type RM Length L Ch R = 1 ,2174.4  ,49.5,80.4,226.7
BEGIN DESCRIPTION:
Downstream Section of Bauer-Hockley
Cross sections extends to limits of Drainage Divide
Cross Section S01-DS
END DESCRIPTION:
XS GIS Cut Line= 3
    2987774.7294   13938639.7181    2986854.0586   13938599.5122
    2986123.2739   13938047.2917
#Sta/Elev= 30
  4283.5   186.5  4313.5     187  4868.5   186.1  4928.5   187.2  4958.5   187.2
  4973.5   186.1  4993.5   181.9  4996.1  180.99  4999.9  178.77    5000  179.75
  5001.9  178.84  5003.5   181.7  5033.5     185  5048.5   186.1  5063.5   186.7
  5093.5   185.7  5123.5   186.2  5153.5     186    5205   186.5    5220   187.5
    5235   187.7    5265   187.3    5325   187.6    5340   188.1    5385   187.2
    5415   187.9    5490   187.8    5535   188.5    6120   189.5    6121   189.5
#Mann= 5 ,-1 , 0
  4283.5      .2       0  4313.5    .045       0  4973.5    .055       0
  5048.5    .045       0    6120      .2       0
#XS Ineff= 2 , 0
       0    4980     186    5010       0     186
Permanent Ineff=
       F       F
Bank Sta=4973.5,5048.5
XS Rating Curve= 0
Exp/Cntr=.5,.3

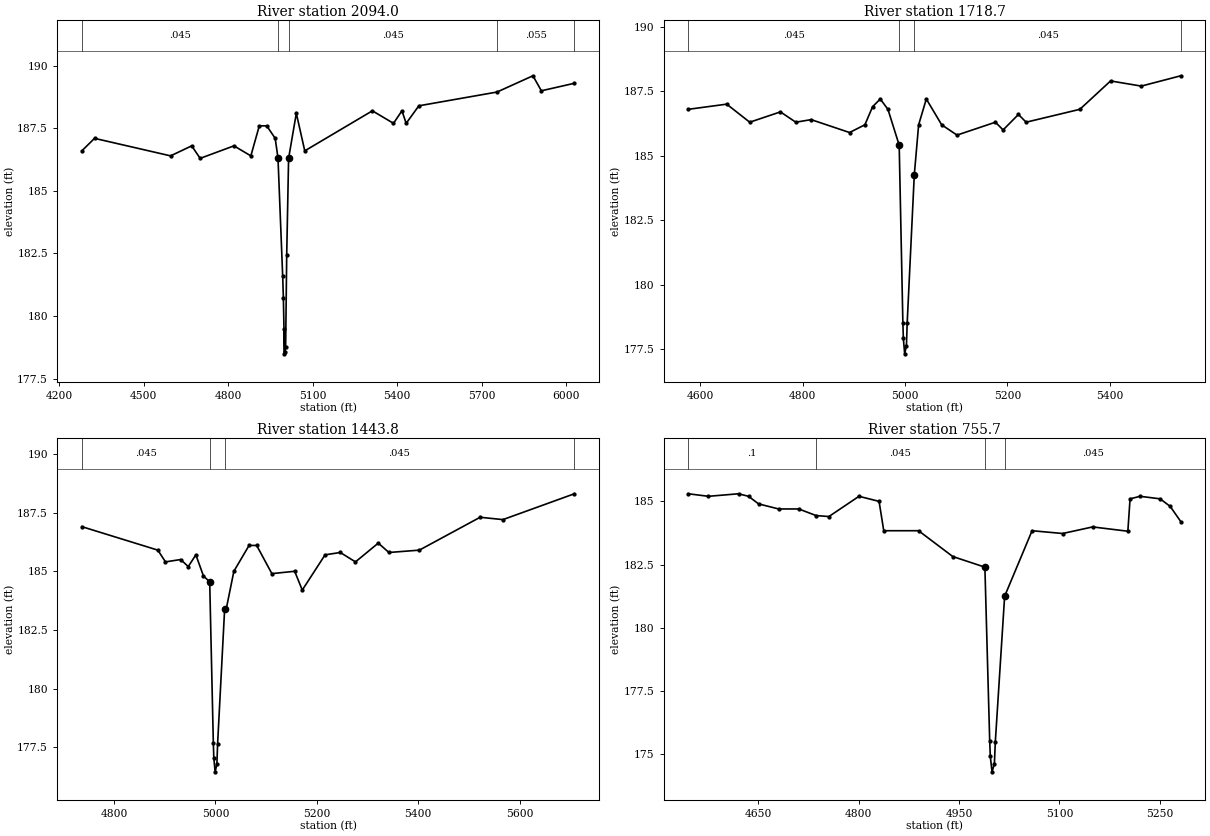
Type RM Length L Ch R = 1 ,2094.0  ,216.7,375.3,326
BEGIN DESCRIPTION:
Cross sections extends to limits of Drainage Divide
Cross Section XS03
END DESCRIPTION:
XS GIS Cut Line= 3
     2987780.907   13938629.5256    2987127.3953   13938568.4141
    2986259.7003   13937905.3152
#Sta/Elev= 30
  4280.6   186.6  4325.6   187.1  4595.6   186.4  4670.6   186.8  4700.6   186.3
  4820.6   186.8  4880.6   186.4  4910.6   187.6    4937   187.6    4967   187.1
  4976.9  186.32  4993.5  181.62  4996.1  180.71  4999.9  178.49    5000  179.47
  5001.9  178.56  5004.1  178.77  5007.9  182.45  5014.6   186.3    5042   188.1
    5072   186.6    5312   188.2    5387   187.7    5417   188.2    5432   187.7
    5477   188.4  5754.4  188.95    5882   189.6    5912     189    6029   189.3
#Mann= 5 ,-1 , 0
  4280.6    .045       0  4976.8    .055       0  5014.6    .045       0
  5754.4    .055       0    6029      .2       0
Bank Sta=4976.9,5014.6
XS Rating Curve= 0
Exp/Cntr=.3,.1

Type RM Length L Ch R = 1 ,1718.7  ,170.4,274.9,289.9
BEGIN DESCRIPTION:
Cross sections extends to limits of Drainage Divide
Cross Section XS02
END DESCRIPTION:
XS GIS Cut Line= 2
      2987783.07   13938617.4055     2986926.494   13938179.1679
#Sta/Elev= 30
  4576.6   186.8  4651.6     187  4696.6   186.3  4756.6   186.7  4786.6   186.3
  4816.6   186.4  4891.6   185.9  4921.6   186.2  4936.6   186.9  4951.6   187.2
  4966.6   186.8  4988.6  185.41  4995.8  178.53  4996.7  177.93  4999.3  177.32
  5002.8  177.64  5004.2  178.51  5018.1  184.26  5026.6   186.2  5041.6   187.2
  5071.6   186.2  5101.6   185.8  5176.6   186.3  5191.6     186  5221.6   186.6
  5236.6   186.3  5341.6   186.8  5401.6   187.9  5461.6   187.7  5538.8   188.1
#Mann= 4 ,-1 , 0
  4576.6    .045       0  4988.6    .055       0  5018.1    .045       0
  5538.8      .2       0
Bank Sta=4988.6,5018.1
XS Rating Curve= 0
Exp/Cntr=.3,.1

Type RM Length L Ch R = 1 ,1443.8  ,583.6,688.1,691.1
BEGIN DESCRIPTION:
Cross Section XS01
END DESCRIPTION:
XS GIS Cut Line= 3
    2987792.8807   13938547.4869    2987432.9326   13938078.7173
    2987052.0573   13938082.9027
#Sta/Elev= 30
  4736.3   186.9  4886.3   185.9  4901.3   185.4  4931.3   185.5  4946.3   185.2
  4961.3   185.7  4976.3   184.8  4988.6  184.55  4995.8  177.67  4996.7  177.07
  4999.3  176.46  5002.8  176.78  5004.2  177.65  5018.1   183.4  5021.3   183.4
  5036.3     185  5066.3   186.1  5081.3   186.1  5111.3   184.9  5156.3     185
  5171.3   184.2  5216.3   185.7  5246.3   185.8  5276.3   185.4  5321.3   186.2
  5342.3   185.8  5402.3   185.9  5522.3   187.3  5567.3   187.2  5708.2   188.3
#Mann= 4 ,-1 , 0
  4736.3    .045       0  4988.6    .055       0  5018.1    .045       0
  5708.2      .2       0
Bank Sta=4988.6,5018.1
XS Rating Curve= 0
Exp/Cntr=.3,.1

Type RM Length L Ch R = 1 ,755.7   ,0,0,0
BEGIN DESCRIPTION:
Xsec extends to limits of Drainage Divide
Cross Section XS0.5
END DESCRIPTION:
XS GIS Cut Line= 2
      2988167.05      13938325.5      2987963.73     13937618.32
#Sta/Elev= 30
  4545.5   185.3  4575.5   185.2  4620.5   185.3  4635.5   185.2  4650.5   184.9
  4680.5   184.7  4710.5   184.7  4736.3  184.44  4755.5   184.4  4800.5   185.2
  4830.5     185  4837.5  183.84  4889.5  183.84  4940.6  182.82  4988.6   182.4
  4995.8  175.52  4996.7  174.92  4999.3  174.31  5002.8  174.63  5004.2   175.5
  5018.1  181.25  5059.1  183.84  5104.8  183.73  5149.6  183.99  5202.2  183.82
  5205.5   185.1  5220.5   185.2  5250.5   185.1  5265.5   184.8  5281.3   184.2
#Mann= 4 ,-1 , 0
  4545.5      .1       0  4736.3    .045       0  4988.6    .055       0
  5018.1    .045       0
#XS Ineff= 2 , 0
       0                    5250       0
Permanent Ineff=
       F       T
Bank Sta=4988.6,5018.1
XS Rating Curve= 0
Exp/Cntr=.3,.1

Chan Stop Cuts=-1